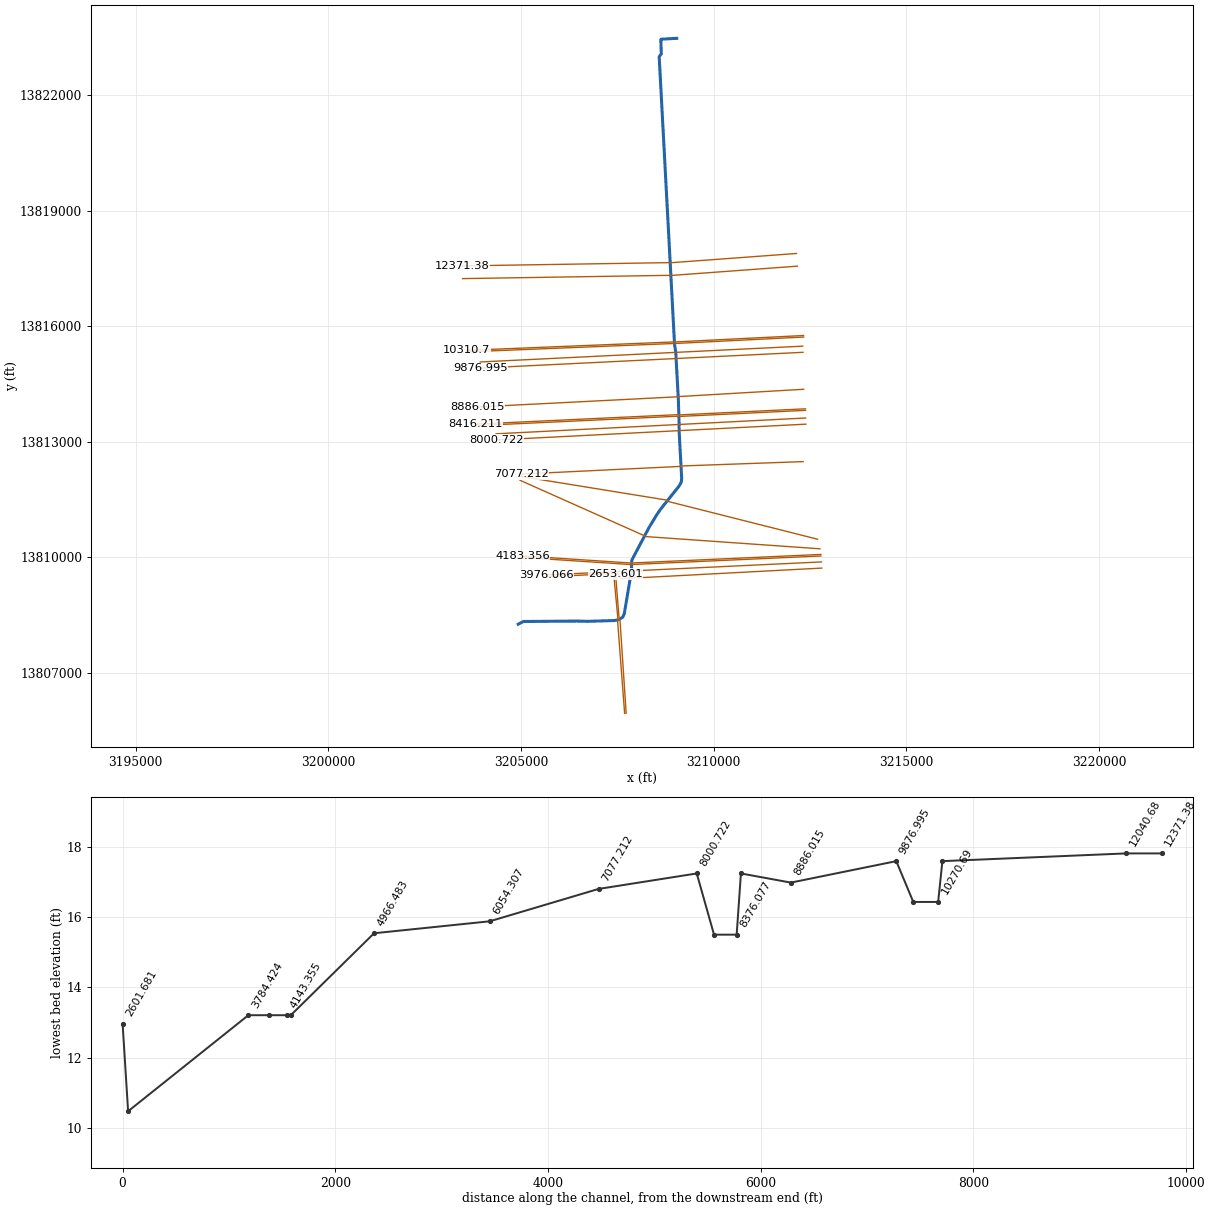
--- B112_02_00.prj (project) ---

Proj Title=B112-02-00
Current Plan=p02
Default Exp/Contr=.3,.1
English Units
Geom File=g02
Geom File=g03
Flow File=f05
Flow File=f06
Plan File=p02
Plan File=p03
Y Axis Title=Elevation
X Axis Title(PF)=Main Channel Distance
X Axis Title(XS)=Station
BEGIN DESCRIPTION:
Armand Bayou
Willow Springs Bayou 1.78
HCFCD Unit B112-02-00
Flood Hazard Model
10, 2, 1, 0.2% Event
Filename B112_02_00.prj
Prepared by: Christopher Moss Date: 6/15/2004
Reviewd by:		Date:
Status FINAL
END DESCRIPTION:
DSS Export Rating Curves= 0
DSS Export Rating Curve Sorted= 0
DSS Export Volume Flow Curves= 0
DXF OffsetX= 0
DXF OffsetY= 0
DXF ScaleX= 1
DXF ScaleY= 10

--- B112_02_00.p02 (plan) ---

Plan Title=FEMA Effective June 2007
Version=Version 3.0.1  Mar 2001
Short Identifier=FEMAeff0607
Geom File=g02
Flow File=f05
Subcritical Flow
K Sum by GR= 0
Std Step Tol= 0.01
Critical Tol= 0.01
Num of Std Step Trials= 20
Max Error Tol= 0.3
Flow Tol Ratio= 0.001
Split Flow NTrial= 30
Split Flow Tol= 0.02
Split Flow Ratio= 0.02
Log Output Level= 0
Friction Slope Method= 0
Unsteady Friction Slope Method= 2
Secant Critical Depth
Global Vel Dist= 0 , 0 , 0
Global Log Level= 0
CheckData=True
Encroach Param=-1 ,0,0, 2
Computation Interval=1HOUR
Output Interval=1HOUR
Run HTab= 0
Run UNet= 0
Run PostProcess= 0
UNET Theta= 1
UNET ZTol= 0.02
UNET ZSATol= 0.1
UNET MxIter= 20
UNET MaxInSteps= 20
UNET DtIC= 0
UNET DtMin= 0
UNET MaxCRTS= 20
UNET WFStab= 2
UNET SFStab= 1
UNET WFX= 1
UNET SFX= 1
UNET Convert EG Bridges=-1
UNET Use Existing IB Tables=-1
Instantaneous Interval=1HOUR
DSS File=dss
Write IC File= 0
Write Velocity= 0
Write Detailed= 0

--- B112_02_00.p03 (plan) ---

Plan Title=Floodway
Version=Version 3.0.1  Mar 2001
Short Identifier=Floodway0607
Geom File=g03
Flow File=f06
Subcritical Flow
K Sum by GR= 0
Std Step Tol= 0.01
Critical Tol= 0.01
Num of Std Step Trials= 20
Max Error Tol= 0.3
Flow Tol Ratio= 0.001
Split Flow NTrial= 30
Split Flow Tol= 0.02
Split Flow Ratio= 0.02
Log Output Level= 0
Friction Slope Method= 0
Unsteady Friction Slope Method= 2
Secant Critical Depth
Global Vel Dist= 0 , 0 , 0
Global Log Level= 0
CheckData=True
Encroach Param=-1 ,0,0, 2
Encroach River=B112-02-00
Encroach Reach=MAIN
Encroach Node=12371.38
       1 3240.43 3336.12
Encroach Node=12040.68
       1 4960.13 5039.87
Encroach Node=10310.7
       1 4962.07 5037.93
Encroach Node=10270.69
       1 4962.07 5037.93
Encroach Node=10153.84
       1 4962.07 5037.93
Encroach Node=10036.99
       1 4952.07 5027.93
Encroach Node=9876.995
       1 4957.07 5032.93
Encroach Node=8886.015
       1 4965.67 5044.33
Encroach Node=8416.211
       1 4958.02 5041.98
Encroach Node=8376.077
       1 4958.02 5041.98
Encroach Node=8269.67
       1 4958.02 5041.98
Encroach Node=8163.272
       1 4973.02 5056.98
Encroach Node=8000.722
       1 4968.02 5051.98
Encroach Node=7077.212
       1 4957.36 5042.64
Encroach Node=6054.307
       1 4961.55 5038.45
Encroach Node=4966.483
       1 4961.56 5038.44
Encroach Node=4183.356
       1 4970.71 5039.29
Encroach Node=4143.355
       1 4965.71 5034.29
Encroach Node=4059.7
       1 4965.71 5034.29
Encroach Node=3976.066
       1 4965.71 5034.29
Encroach Node=3784.424
       1 4965.71 5034.29
Encroach Node=2653.601
       1 4966.14 5013.86
Encroach Node=2601.681
       1 4976.14 5023.86
Encroach Node=2541.7
       1 4976.14 5023.86
Encroach Node=2481.7
       1 4976.14 5023.86
Encroach Node=2321.654
       1    4973 5023.86
Encroach Node=1966.901
       1 4960.64 5029.36
Encroach Node=1926.803
       1 4960.64 5029.36
Encroach Node=1827.1
       1 4960.64 5029.36
Encroach Node=1727.347
       1 4960.64    5015
Encroach Node=1566.873
       1 4969.93 5030.07
Encroach Node=1405.496
       1 4969.93 5030.07
Encroach Node=641.317
       1 4966.74 5043.26
Encroach Node=621.038
       1    4942 5038.26
Encroach Node=532.5
       1    4942 5038.26
Encroach Node=444.025
       1    4942 5038.26
Encroach Node=364.024
       1 4961.74    5053
Encroach Reach=B112-02-00_0004
Encroach Node=12371.38
       1 3240.43 3336.12
Encroach Node=12040.68
       1 4960.13 5039.87
Encroach Node=10310.7
       1 4962.07 5037.93
Encroach Node=10270.69
       1 4962.07 5037.93
Encroach Node=10153.84
       1 4962.07 5037.93
Encroach Node=10036.99
       1 4952.07 5027.93
Encroach Node=9876.995
       1 4957.07 5032.93
Encroach Node=8886.015
       1 4965.67 5044.33
Encroach Node=8416.211
       1 4958.02 5041.98
Encroach Node=8376.077
       1 4958.02 5041.98
Encroach Node=8269.67
       1 4958.02 5041.98
Encroach Node=8163.272
       1 4973.02 5056.98
Encroach Node=8000.722
       1 4968.02 5051.98
Encroach Node=7077.212
       1 4957.36 5042.64
Encroach Node=6054.307
       1 4961.55 5038.45
Encroach Node=4966.483
       1 4961.56 5038.44
Encroach Node=4183.356
       1 4970.71 5039.29
Encroach Node=4143.355
       1 4965.71 5034.29
Encroach Node=4059.7
       1 4965.71 5034.29
Encroach Node=3976.066
       1 4965.71 5034.29
Encroach Node=3784.424
       1 4965.71 5034.29
Encroach Node=2653.601
       1 4966.14 5013.86
Encroach Node=2601.681
       1 4976.14 5023.86
Encroach Node=2541.7
       1 4976.14 5023.86
Encroach Node=2481.7
       1 4976.14 5023.86
Encroach Node=2321.654
       1    4973 5023.86
Encroach Node=1966.901
       1 4960.64 5029.36
Encroach Node=1926.803
       1 4960.64 5029.36
Encroach Node=1827.1
       1 4960.64 5029.36
Encroach Node=1727.347
       1 4960.64    5015
Encroach Node=1566.873
       1 4969.93 5030.07
Encroach Node=1405.496
       1 4969.93 5030.07
Encroach Node=641.317
       1 4966.74 5043.26
Encroach Node=621.038
       1    4942 5038.26
Encroach Node=532.5
       1    4942 5038.26
Encroach Node=444.025
       1    4942 5038.26
Encroach Node=364.024
       1 4961.74    5053
Computation Interval=1HOUR
Output Interval=1HOUR
Run HTab= 0
Run UNet= 0
Run PostProcess= 0
UNET Theta= 1
UNET ZTol= 0.02
UNET ZSATol= 0.1
UNET MxIter= 20
UNET MaxInSteps= 20
UNET DtIC= 0
UNET DtMin= 0
UNET MaxCRTS= 20
UNET WFStab= 2
UNET SFStab= 1
UNET WFX= 1
UNET SFX= 1
UNET Convert EG Bridges=-1
UNET Use Existing IB Tables=-1
Instantaneous Interval=1HOUR
Write IC File= 0
Write Velocity= 0
Write Detailed= 0

--- B112_02_00.f05 (steady flow) ---

Flow Title=FEMA Effective June 2007
Version=Version 3.0.1  Mar 2001
Number of Profiles= 4
Profile Names=10PCT_10yr, 2PCT_50yr, 1PCT_100yr, 0.2PCT_500yr
River Rch & RM=B112-02-00,B112-02-00_0004            ,12371.38
     428     658     778    1138
River Rch & RM=B112-02-00,B112-02-00_0004            ,12040.68
     428     658     778    1138
River Rch & RM=B112-02-00,B112-02-00_0004            ,10310.7
     439     674     797    1166
River Rch & RM=B112-02-00,B112-02-00_0004            ,9876.995
     464     713     843    1232
River Rch & RM=B112-02-00,B112-02-00_0004            ,8886.015
     483     742     878    1283
River Rch & RM=B112-02-00,B112-02-00_0004            ,8163.272
     487     749     886    1294
River Rch & RM=B112-02-00,B112-02-00_0004            ,8000.722
     513     788     932    1363
River Rch & RM=B112-02-00,B112-02-00_0004            ,7077.212
     543     835     987    1443
River Rch & RM=B112-02-00,B112-02-00_0004            ,6054.307
     577     887    1049    1533
River Rch & RM=B112-02-00,B112-02-00_0004            ,4966.483
     605     929    1098    1606
River Rch & RM=B112-02-00,B112-02-00_0004            ,4143.355
     617     947    1121    1638
River Rch & RM=B112-02-00,B112-02-00_0004            ,3784.424
     657    1009    1194    1745
River Rch & RM=B112-02-00,B112-02-00_0004            ,2653.601
      81     195     259     456
River Rch & RM=B112-02-00,B112-02-00_0004            ,2601.681
      86     202     268     470
River Rch & RM=B112-02-00,B112-02-00_0004            ,2321.654
      93     213     281     489
River Rch & RM=B112-02-00,B112-02-00_0004            ,1926.803
     103     229     300     517
River Rch & RM=B112-02-00,B112-02-00_0004            ,1405.496
     120     254     329     559
River Rch & RM=B112-02-00,B112-02-00_0004            ,641.317
     126     264     341     576
Boundary for River Rch & Prof#=B112-02-00,B112-02-00_0004            , 1
Up Type= 0
Dn Type= 3
Dn Slope=.000638
DSS Import GetInterval= 0
DSS Import GetPeak= 0
DSS Import FillOption= 0

--- B112_02_00.f06 (steady flow) ---

Flow Title=Floodway
Version=Version 3.0.1  Mar 2001
Number of Profiles= 2
Profile Names=1PCT_100yr, 1PCTFloodway_100yrFW
River Rch & RM=B112-02-00,B112-02-00_0004            ,12371.38
     778     778
River Rch & RM=B112-02-00,B112-02-00_0004            ,12040.68
     778     778
River Rch & RM=B112-02-00,B112-02-00_0004            ,10310.7
     797     797
River Rch & RM=B112-02-00,B112-02-00_0004            ,9876.995
     843     843
River Rch & RM=B112-02-00,B112-02-00_0004            ,8886.015
     878     878
River Rch & RM=B112-02-00,B112-02-00_0004            ,8163.272
     886     886
River Rch & RM=B112-02-00,B112-02-00_0004            ,8000.722
     932     932
River Rch & RM=B112-02-00,B112-02-00_0004            ,7077.212
     987     987
River Rch & RM=B112-02-00,B112-02-00_0004            ,6054.307
    1049    1049
River Rch & RM=B112-02-00,B112-02-00_0004            ,4966.483
    1098    1098
River Rch & RM=B112-02-00,B112-02-00_0004            ,4143.355
    1121    1121
River Rch & RM=B112-02-00,B112-02-00_0004            ,3784.424
    1194    1194
River Rch & RM=B112-02-00,B112-02-00_0004            ,2653.601
     259     259
River Rch & RM=B112-02-00,B112-02-00_0004            ,2601.681
     268     268
River Rch & RM=B112-02-00,B112-02-00_0004            ,2321.654
     281     281
River Rch & RM=B112-02-00,B112-02-00_0004            ,1926.803
     300     300
River Rch & RM=B112-02-00,B112-02-00_0004            ,1405.496
     329     329
River Rch & RM=B112-02-00,B112-02-00_0004            ,641.317
     341     341
Boundary for River Rch & Prof#=B112-02-00,B112-02-00_0004            , 1
Up Type= 0
Dn Type= 3
Dn Slope=.000638
DSS Import GetInterval= 0
DSS Import GetPeak= 0
DSS Import FillOption= 0

--- B112_02_00.g02 (geometry) ---

Geom Title=B112-02-00 June 2007
Version=Version 3.0.1  Mar 2001

River Reach=B112-02-00      ,B112-02-00_0004
Reach XY= 30
      3209040.75       13823469.      3208644.75       13823448.
       3208627.5       13823439.       3208640.5       13823067.
      3208585.25       13822991.      3208984.75       13815513.
       3209014.5       13815339.        3209083.       13814087.
       3209103.5       13813437.      3209096.75       13813381.
      3209105.75       13813345.       3209102.5       13813272.
       3209169.5       13812049.      3209156.25       13811946.
      3209103.25       13811853.        3208623.       13811253.
      3208511.75       13811088.        3208328.       13810787.
        3207884.       13809946.      3207869.25       13809882.
      3207869.25       13809714.      3207827.25       13809413.
       3207678.5       13808534.      3207636.25       13808446.
      3207530.75       13808382.      3207422.25       13808361.
      3206730.75       13808340.      3206453.25       13808347.
      3205059.75       13808336.      3204926.75       13808266.

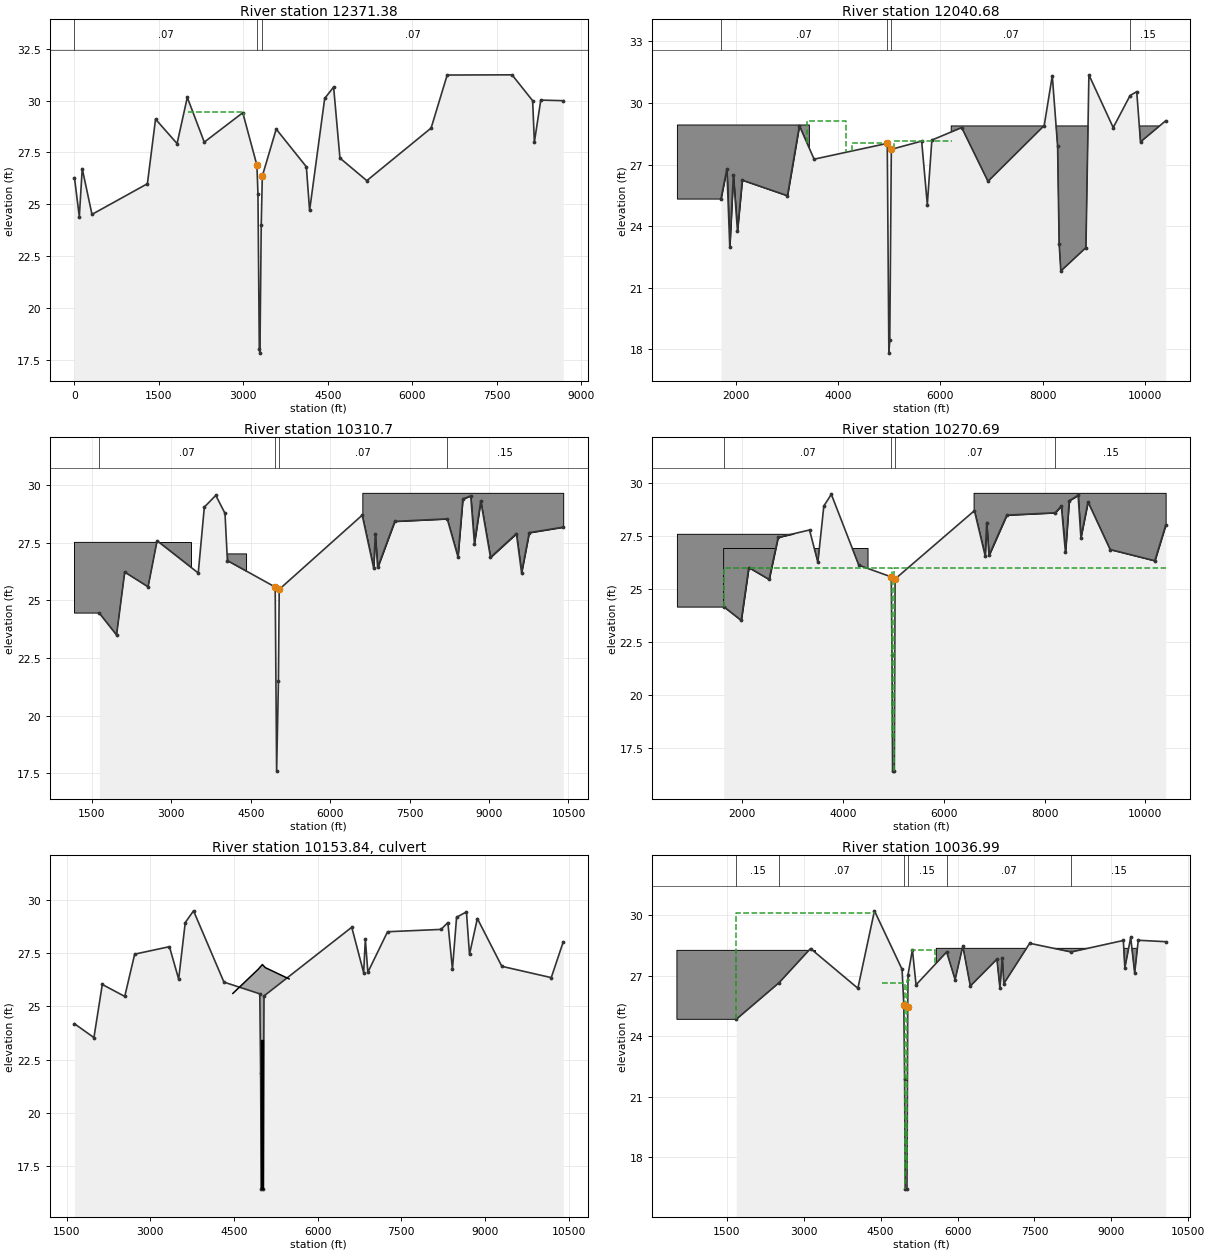
Type RM Length L Ch R = 1 ,12371.38,330.21,330.69,330.25
BEGIN DESCRIPTION:
CROSS SECTION ADDED TO EXTEND FLOODWAY TO EXISTING
END DESCRIPTION:
XS GIS Cut Line= 4
     3212148.281    13817886.223     3208916.632    13817647.871
     3208846.439    13817648.652     3203477.662    13817563.855
#Sta/Elev= 30
       0   26.28   86.01    24.4  137.76   26.72  310.95   24.51 1294.93   25.99
 1439.68   29.11  1822.3   27.93 2003.77   30.16 2305.42      28 2988.88   29.42
 3240.43   26.88 3258.59   25.51 3282.58      18 3293.77   17.81 3316.91      24
 3336.12   26.36 3582.89   28.63 4118.06   26.81 4175.91    24.7 4444.01   30.11
 4602.56   30.66 4714.74   27.23 5192.09   26.14 6334.15   28.68 6619.35   31.24
  7771.5   31.25  8137.4      30 8167.85      28 8281.79   30.03 8680.07      30
#Mann= 3 , 0 , 0
       0     .07       0 3240.43    .032       0 3336.12     .07       0
#XS Ineff= 1 ,-1
 2013.65 3003.41   29.46
Permanent Ineff=
       F
#Block Obstruct= 2 , 0
         2025.03    29.9 3581.37           28.62
Bank Sta=3240.43,3336.12
XS Rating Curve= 0
Exp/Cntr=.3,.1

Type RM Length L Ch R = 1 ,12040.68,1730.24,1729.98,1733.32
XS GIS Cut Line= 4
     3212172.554    13817557.117     3208926.952    13817317.736
      3208847.21    13817318.623     3203482.874    13817233.896
#Sta/Elev= 30
 1707.37   25.34 1822.57   26.79 1879.23   22.97 1949.59   26.49 2029.64   23.77
 2122.89   26.24 3007.29   25.48  3240.6   28.89 3528.82   27.26 4960.13   28.03
 4991.66   17.81 5009.54   18.45 5039.87   27.74 5633.31   28.14 5743.86   25.05
 5832.69   28.19 6416.25    28.8  6931.1   26.18    8031    28.9 8188.86   31.33
 8292.99    27.9    8323   23.15 8355.96   21.81 8847.24   22.95 8905.14   31.37
 9380.94    28.8 9710.61   30.36 9840.95   30.55 9914.94    28.110406.54   29.13
#Mann= 4 ,-1 , 0
 1707.37     .07       0 4960.13    .032       0 5039.87     .07       0
 9710.61     .15       0
#XS Ineff= 3 ,-1
 3386.87 4151.59   29.14 4277.94 4956.22   28.03 5084.75 6226.86   28.15
Permanent Ineff=
       F       F       F
#Block Obstruct= 2 ,-1
  844.85 3426.34   28.95 6211.2110406.54   28.88
Bank Sta=4960.13,5039.87
XS Rating Curve= 0
Exp/Cntr=.3,.1

Type RM Length L Ch R = 1 ,10310.7 ,40,40.01,40
XS GIS Cut Line= 4
     3212332.167    13815757.192     3209017.696    13815591.473
     3208942.058    13815589.483     3203580.704     13815371.83
#Sta/Elev= 30
 1640.52   24.45 1966.56    23.5 2120.88   26.23 2561.84   25.59    2732   27.59
 3509.15   26.19    3624   29.05 3839.99   29.56 4014.24   28.78 4059.55   26.73
 4962.07   25.58 4989.25   17.59  5023.4   21.52 5037.93   25.48 6605.11    28.7
 6822.17    26.4 6852.19   27.87 6897.23   26.43 7219.46   28.43 8210.55   28.54
 8413.48   26.89 8505.33    29.4  8654.3   29.54 8724.32   27.47  8843.9   29.32
 9027.61   26.87 9516.91    27.9 9614.47    26.2 9758.85   27.9410400.57   28.18
#Mann= 4 ,-1 , 0
 1640.52     .07       0 4962.07    .032       0 5037.93     .07       0
 8210.55     .15       0
#Block Obstruct= 3 ,-1
 1172.03 3367.72   27.52 3880.05 4411.99   27.04 6607.5110400.57   29.67
Bank Sta=4962.07,5037.93
XS Rating Curve= 0
Exp/Cntr=.5,.3

Type RM Length L Ch R = 1 ,10270.69,231.56,233.7,233.78
XS GIS Cut Line= 4
     3212334.164    13815717.242     3209019.221    13815551.499
     3208943.396    13815549.504     3203582.327    13815331.863
#Sta/Elev= 30
 1640.38   24.18 1988.98   23.53 2139.01   26.02 2541.42   25.46 2719.53   27.44
  3342.4   27.79 3507.93   26.27 3625.86   28.92  3774.5   29.47 4319.57   26.13
 4962.07   25.58 4977.21   21.89 4988.29   16.43  5023.4   16.43 5037.93   25.48
 6610.59    28.7 6824.03   26.57 6854.05   28.14 6899.09   26.59 7252.31   28.49
  8210.7    28.6 8333.54   28.92 8415.34   26.73 8489.68   29.17 8666.28   29.42
 8721.19   27.43 8862.05   29.11 9300.47   26.8710186.59   26.34 10400.8   28.01
#Mann= 4 ,-1 , 0
 1640.38     .07       0 4962.07    .032       0 5037.93     .07       0
  8210.7     .15       0
#XS Ineff= 2 , 0
       0    4985      26    5015       0      26
Permanent Ineff=
       F       F
#Block Obstruct= 3 ,-1
   713.8 3321.01   27.61 1640.38 4502.02   26.92 6593.86 10400.8   29.54
Bank Sta=4962.07,5037.93
XS Rating Curve= 0
Exp/Cntr=.5,.3

Type RM Length L Ch R = 2 ,10153.84,,,
Node Photo=G:\C2001-041_Harris_County_FEMA\1-Armand_Bayou\Willow Springs Bayou Trib 1.78\Survey info\South Pasadena BLVD - 3367\MVC-016S.JPG
BEGIN DESCRIPTION:
Pasadena Blvd.
END DESCRIPTION:
Bridge Culvert--1,0,-1,-1, 0
Deck Dist Width WeirC Skew NumUp NumDn MinLoCord MaxHiCord MaxSubmerge Is_Ogee
85,85,2.6,0, 5, 5, , , .95, 0, 0,0,,
  4479.64934.3665008.4175060.859    5487
    25.6 26.7333 26.9537 26.8085   26.28
       0       0       0       0       0
  4479.64934.3665008.4175060.859    5487
    25.6 26.7333 26.9537 26.8085   26.28
       0       0       0       0       0
BR Coef=-1 , 0 , 0 ,, 0 ,,,.8,-1,,0,
WSPro=,,,, 1 ,,,, 0 ,,,, 0 ,,,,-1 ,-1 ,-1 , 0 , 0 , 0 , 0 , 0
Multiple Barrel Culv=2,7,7,85,.012,.2,1,58,1,16.43,16.43, 3,Culvert #1  , 0 ,85
  4991.8  4991.8    5000    5000  5008.2  5008.2
Culvert Bottom n=.012
BC Design=,, 0 ,, 0 ,,,,,,
BC HTab HWMax=29.47

Type RM Length L Ch R = 1 ,10036.99,160.01,160,160
XS GIS Cut Line= 2
     3212309.301    13815481.042     3203942.843    13815070.799
#Sta/Elev= 30
 1682.91   24.85 2520.56   26.67 3131.91   28.36 4055.67   26.39 4378.92   30.23
 4917.63   27.33 4952.07   25.58 4967.21   21.89 4979.25   16.43  5013.4   16.43
 5027.93   25.48 5034.26   27.07 5119.22    28.3 5190.26   26.56  5787.4   28.19
 5952.55   26.82 6102.96   28.48 6248.81    26.5 6768.21   27.83 6827.23    26.4
 6874.76    27.9 6902.97   26.62 7407.38   28.62 8216.59   28.19 9234.46   28.76
 9263.83   27.39 9377.76   28.91  9455.6   27.15 9525.54   28.7710059.42    28.7
#Mann= 6 ,-1 , 0
 1682.91     .15       0 2520.56     .07       0 4952.07    .032       0
 5027.93     .15       0  5787.4     .07       0 8216.59     .15       0
#XS Ineff= 4 ,-1
  563.23  4380.7   30.14 4521.28 4981.04   26.64    5015    5110    26.8
 5112.73 5556.94   28.27
Permanent Ineff=
       F       F       F       F
#Block Obstruct= 2 ,-1
  525.22  3210.9   28.27 5585.4210088.54   28.37
Bank Sta=4952.07,5027.93
XS Rating Curve= 0
Exp/Cntr=.5,.3

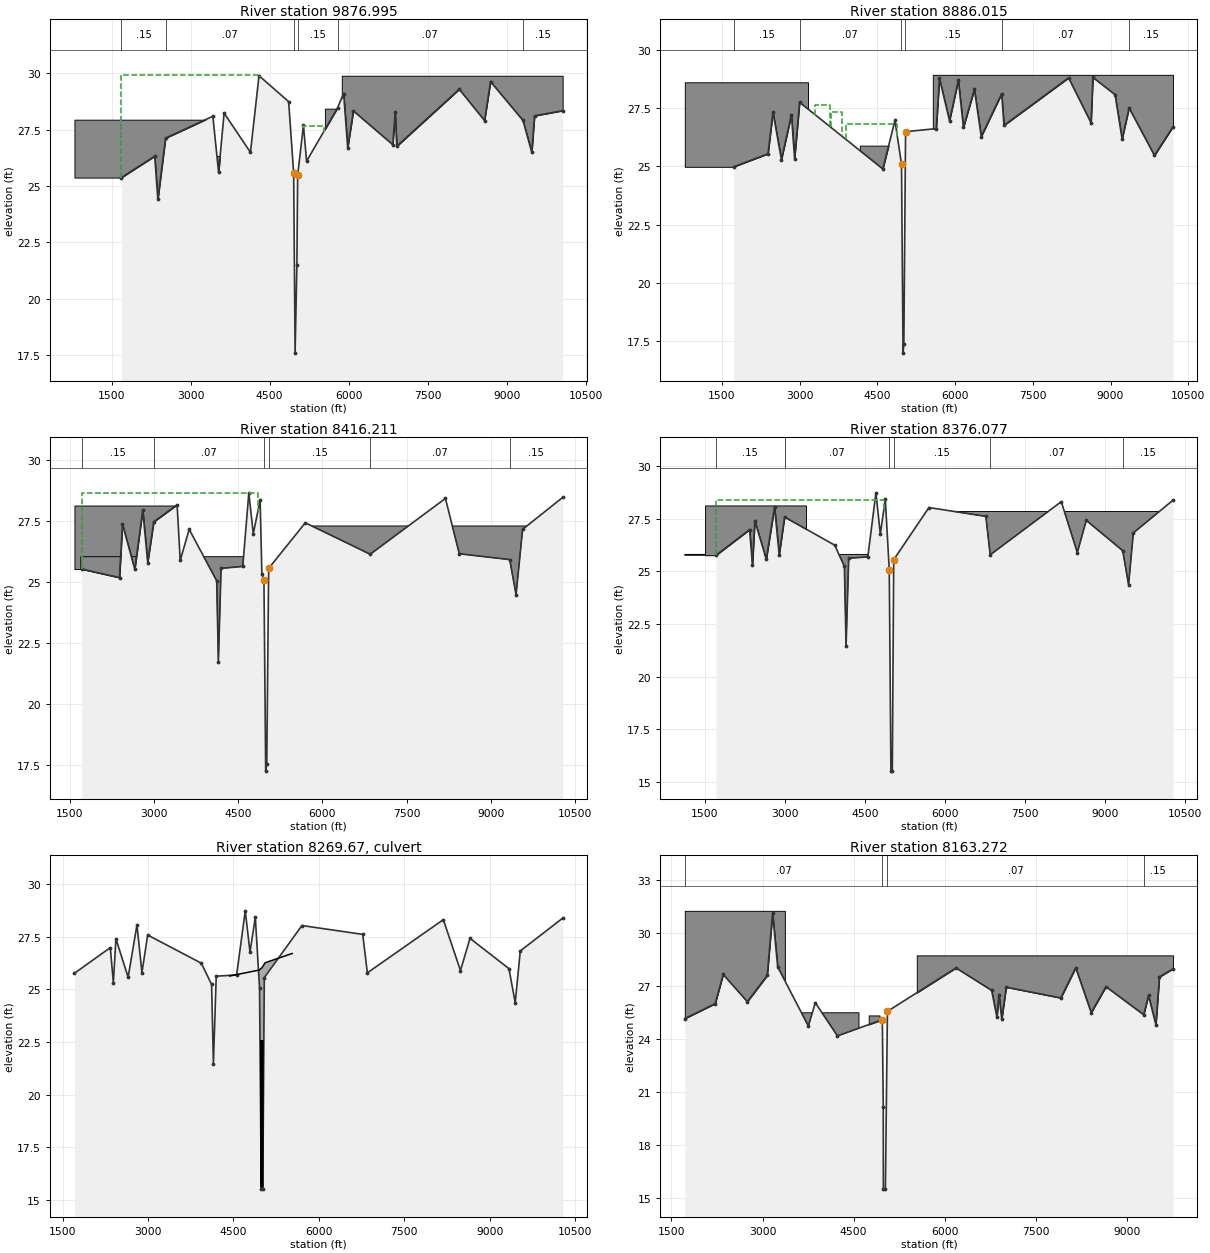
Type RM Length L Ch R = 1 ,9876.995,989.34,990.98,994.01
XS GIS Cut Line= 2
     3212317.137    13815321.234     3203950.679    13814910.991
#Sta/Elev= 30
 1687.09   25.38 2318.83   26.33  2378.9   24.41 2524.74   27.13 3423.01    28.1
 3532.07   25.61 3636.62   28.24 4136.77    26.5 4299.05    29.9 4861.77   28.75
 4957.07   25.58 4984.25   17.59  5018.4   21.52 5032.93   25.48 5142.74    27.7
 5202.29   26.11 5791.58   28.48 5905.34   29.11 5983.23    26.7 6091.22   28.34
 6839.25   26.84 6884.31   28.28 6914.34   26.77 8100.53    29.3 8581.34   27.91
 8694.86   29.64 9309.71   27.92 9477.92    26.5 9530.16   28.12 10063.6   28.35
#Mann= 6 ,-1 , 0
 1687.09     .15       0 2524.74     .07       0 4957.07    .032       0
 5032.93     .15       0 5791.58     .07       0 9309.71     .15       0
#XS Ineff= 2 ,-1
  782.27 4318.12   29.94 5137.39 5525.45   27.67
Permanent Ineff=
       F       F
#Block Obstruct= 4 ,-1
  795.25  3408.5   27.95  3379.4 3598.44   26.34  5549.8 5845.45   28.44
 5870.31 10063.6    29.9
Bank Sta=4957.07,5032.93
XS Rating Curve= 0
Exp/Cntr=.3,.1

Type RM Length L Ch R = 1 ,8886.015,474.5,469.8,462.48
XS GIS Cut Line= 4
     3212334.164    13814362.199     3209107.125     13814173.46
      3209028.92    13814164.946     3203868.253     13813902.23
#Sta/Elev= 30
 1727.27   24.98 2389.09   25.54 2484.45   27.33 2647.51   25.29 2840.58   27.22
 2902.28   25.33 2999.06   27.75 4604.71   24.89 4839.65   26.97 4965.67   25.09
 4995.43   16.98 5011.22   17.38 5044.33   26.49 5637.03   26.62 5697.78   28.78
 5892.36   26.96 6062.94    28.7 6161.27   26.67 6372.98   28.31 6504.84   26.28
  6899.2   28.12 6943.72   26.76 8190.33    28.8 8624.65   26.87 8660.62   28.82
 9087.52   28.08 9224.34   26.17 9357.98   27.51 9847.85   25.4710205.84    26.7
#Mann= 6 ,-1 , 0
 1727.27     .15       0 2999.06     .07       0 4949.13    .032       0
 5033.91     .15       0  6899.2     .07       0 9357.98     .15       0
#XS Ineff= 3 ,-1
 3293.18 3587.93   27.64  3601.8  3816.8   27.33 3886.15 4884.84   26.83
Permanent Ineff=
       F       F       F
#Block Obstruct= 3 ,-1
  782.27 3160.36   28.61 4161.98 4744.93   25.89 5569.9710205.84   28.93
Bank Sta=4965.67,5044.33
XS Rating Curve= 0
Exp/Cntr=.3,.1

Type RM Length L Ch R = 1 ,8416.211,40.17,40.13,40
XS GIS Cut Line= 4
     3212381.958    13813855.162     3209138.762    13813698.281
      3209054.95    13813702.879     3203816.654    13813457.354
#Sta/Elev= 30
 1707.21   25.53 2383.33   25.18 2436.12   27.37 2655.95   25.53 2797.52   27.95
 2885.92    25.8 2993.46   27.47 3409.89   28.17 3465.89   25.89 3625.16   27.16
 4115.82   25.05 4145.86   21.72 4193.97   25.56 4580.35   25.64 4688.22   28.65
 4768.02   26.98 4889.97   28.36  4921.3   25.32 4958.02   25.09 4988.99   17.24
 5008.45   17.53 5041.98   25.56 5695.23   27.43  6852.2   26.14 8192.89   28.43
 8439.93   26.16 9338.94   25.92 9451.89   24.48 9568.26   27.1610282.19   28.47
#Mann= 6 ,-1 , 0
 1707.21     .15       0 2993.46     .07       0 4958.02    .032       0
 5041.98     .15       0  6852.2     .07       0 9338.94     .15       0
#XS Ineff= 1 ,-1
 1580.18 4850.07   28.66
Permanent Ineff=
       F
#Block Obstruct= 3 ,-1
 1580.18 3395.05   28.14 1693.36 4836.23   26.04 5694.7610297.78    27.3
Bank Sta=4958.02,5041.98
XS Rating Curve= 0
Exp/Cntr=.5,.3

Type RM Length L Ch R = 1 ,8376.077,208.91,212.8,216.62
XS GIS Cut Line= 4
     3212383.891    13813815.209     3209138.632    13813658.228
     3209054.791    13813662.828     3203818.527    13813417.398
#Sta/Elev= 30
 1707.19   25.77    2337   26.99 2390.72   25.32 2435.77   27.41 2649.93   25.58
 2805.21   28.07 2892.51    25.8 2993.45   27.59 3934.69   26.25 4116.15   25.24
 4147.77   21.46 4197.56   25.63 4555.68   25.69 4707.68   28.74 4790.48   26.78
 4883.95   28.43 4958.02   25.09 4988.99    15.5 5015.45    15.5 5041.98   25.56
 5702.91   28.04 6770.68   27.62 6852.21   25.79  8186.3   28.32 8487.62    25.9
 8654.94   27.43 9338.97   25.99 9449.37   24.37 9538.02   26.8310282.22   28.39
#Mann= 6 ,-1 , 0
 1707.19     .15       0 2993.45     .07       0 4958.02    .032       0
 5041.98     .15       0 6852.21     .07       0 9338.97     .15       0
#XS Ineff= 2 ,-1
  1345.5 4850.07   28.41 5041.9810282.22   25.56
Permanent Ineff=
       F       F
#Block Obstruct= 3 ,-1
 1120.92  4844.5   25.81 1501.96 3395.05   28.14 5761.0910282.22   27.85
Bank Sta=4958.02,5041.98
XS Rating Curve= 0
Exp/Cntr=.5,.3

Type RM Length L Ch R = 2 ,8269.67 ,,,
Node Photo=G:\C2001-041_Harris_County_FEMA\1-Armand_Bayou\Willow Springs Bayou Trib 1.78\Survey info\Aaron - 3380\MVC-023S.JPG
BEGIN DESCRIPTION:
Aaron St.
END DESCRIPTION:
Bridge Culvert--1,0,-1,-1, 0
Deck Dist Width WeirC Skew NumUp NumDn MinLoCord MaxHiCord MaxSubmerge Is_Ogee
106,25,2.6,0, 5, 5, , , .95, 0, 0,0,,
    4434    4949    5000    5057    5531
   25.64   25.92   26.03   26.27   26.71
                                        
    4434    4949    5000    5057    5531
   25.64   25.92   26.03   26.27   26.71
                                        
BR Coef=-1 , 0 , 0 ,, 0 ,,,.8,-1,,0,
WSPro=,,,, 1 ,,,, 0 ,,,, 0 ,,,,-1 ,-1 ,-1 , 0 , 0 , 0 , 0 , 0
Multiple Barrel Culv=1,7,,60.5,.025,.9,1,2,3,15.59,15.59, 4,Culvert #1  , 0 ,85
  4987.5  4997.5  4995.5  5005.5  5004.5  5014.5  5012.5  5022.5
Culvert Bottom n=.025
BC Design=,, 0 ,, 0 ,,,,,,
BC HTab HWMax=28.74

Type RM Length L Ch R = 1 ,8163.272,160.01,162.55,160
XS GIS Cut Line= 2
     3212383.891    13813616.304     3204353.085    13813206.061
#Sta/Elev= 30
 1719.16   25.15  2220.1      26 2351.67   27.65 2748.98   26.11 3077.26   27.59
 3165.62   31.12  3249.2   28.08 3754.54   24.73 3868.96   26.05 4234.37   24.17
 4973.02   25.09 4988.42   20.17    4990    15.5 5023.45    15.5 5056.98   25.56
 6186.82   28.02 6773.47   26.75 6860.64   25.22 6893.63   26.51 6940.29   25.11
 7013.79   26.93 7912.97   26.32 8158.22   28.03 8413.39   25.49 8656.77   26.96
 9277.96   25.37 9357.45   26.46 9478.97    24.8 9537.07   27.51 9760.44   27.97
#Mann= 4 ,-1 , 0
 1719.16     .07       0 4973.02    .032       0 5056.98     .07       0
 9277.96     .15       0
#XS Ineff= 2 , 0
       0 4973.02   25.09 5056.98       0   25.56
Permanent Ineff=
       F       F
#Block Obstruct= 4 ,-1
 1719.16 3367.46   31.25  3414.3 4588.39   25.48 4748.57 4927.73   25.33
 5540.39 9760.44   28.73
Bank Sta=4973.02,5056.98
XS Rating Curve= 0
Exp/Cntr=.5,.3

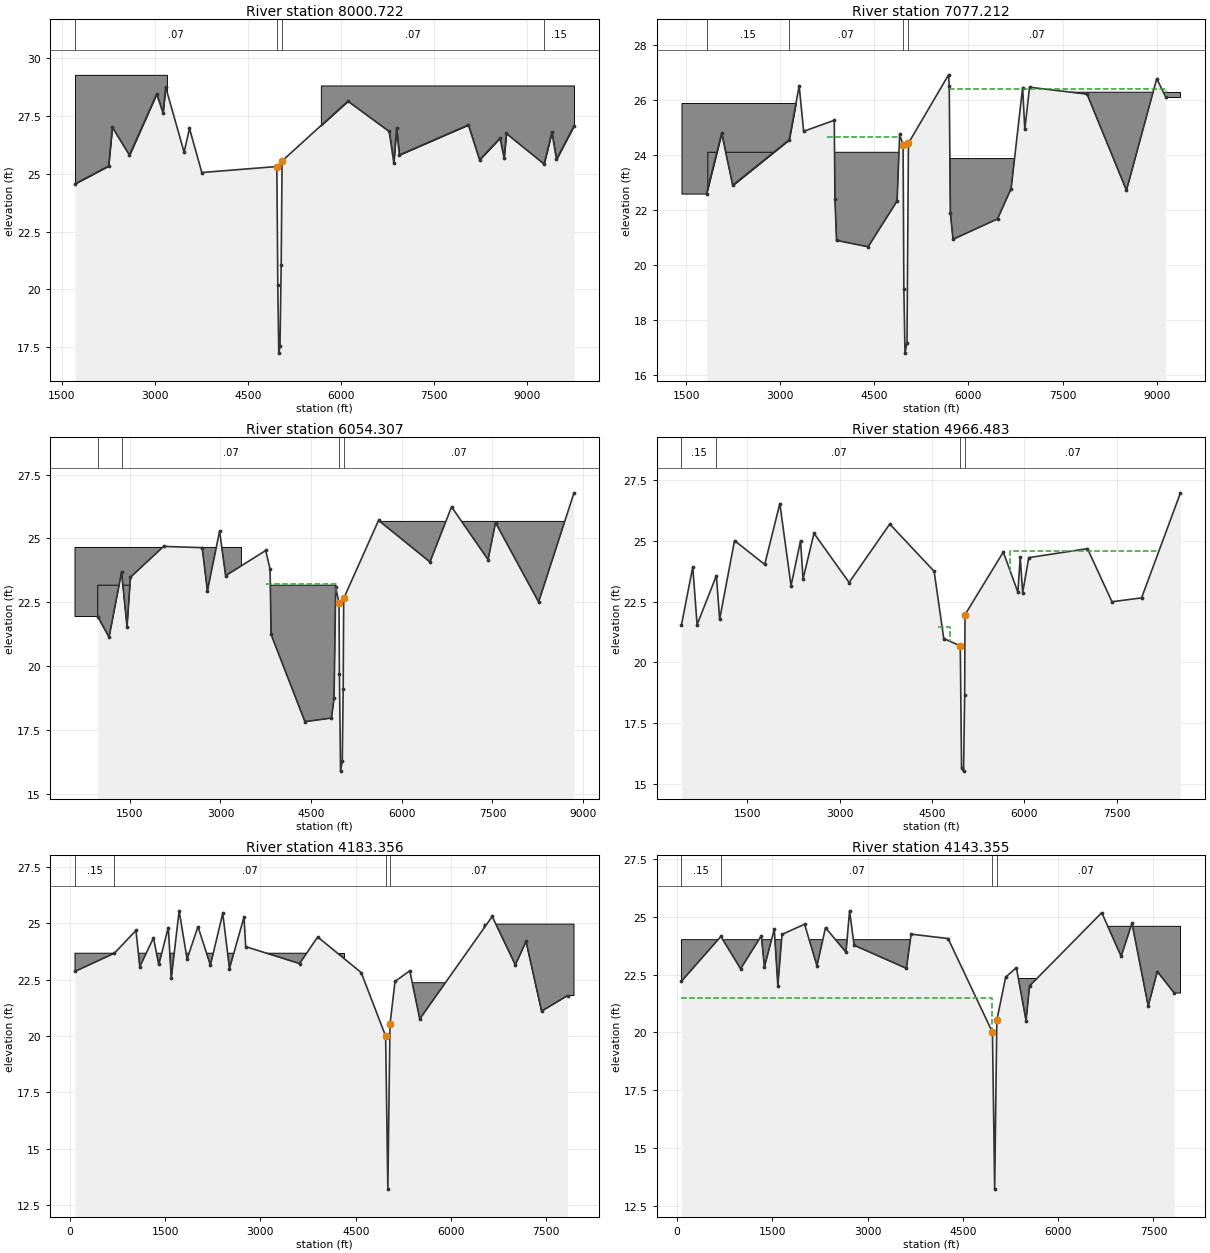
Type RM Length L Ch R = 1 ,8000.722,921.45,923.51,928.02
XS GIS Cut Line= 2
     3212392.053    13813456.512     3204361.248     13813046.27
#Sta/Elev= 30
 1715.14   24.57 2256.74   25.34 2316.82   27.02  2592.5   25.81 3031.43   28.46
 3133.88   27.64 3176.34   28.76 3473.33   25.94 3560.23   26.97  3758.7   25.06
 4968.02   25.32 4983.42   20.17 4998.99   17.24 5018.45   17.53 5037.98   21.04
 5051.98   25.56 6112.77   28.15 6777.63   26.84 6852.73   25.48 6897.79      27
 6941.52   25.82 8053.89   27.12 8234.54   25.61 8563.65   26.55 8629.73   25.69
 8666.88   26.75 9273.94   25.43 9400.15    26.8 9474.03   25.63 9756.42   27.08
#Mann= 4 ,-1 , 0
 1715.14     .07       0 4968.02    .032       0 5051.98     .07       0
 9273.94     .15       0
#Block Obstruct= 3 ,-1
 1715.14 3196.81   29.29 4170.04  4858.3   24.95 5676.91 9756.42   28.83
Bank Sta=4968.02,5051.98
XS Rating Curve= 0
Exp/Cntr=.3,.1

Type RM Length L Ch R = 1 ,7077.212,1044.07,1022.91,971.96
XS GIS Cut Line= 4
     3212321.733    13812485.029     3209192.183    13812372.523
     3209107.927    13812359.364     3205011.959    13812161.808
#Sta/Elev= 30
 1824.18   22.59  2064.5   24.78 2241.09   22.89 3141.34   24.54 3300.71    26.5
  3372.1   24.85 3859.98   25.25 3871.08   22.39 3896.52   20.89 4400.25   20.66
 4861.72   22.32 4902.46   24.74 4957.36   24.35 4969.83   19.13 4987.78    16.8
 5019.52   17.17 5042.64   24.42 5682.44    26.9 5693.01   26.51 5711.55   21.88
 5753.54   20.93 6463.37   21.67 6679.83   22.77 6863.48   26.44  6898.4   24.92
 6973.66   26.45  7890.3    26.2 8519.16   22.71 9001.76   26.76 9141.76   26.11
#Mann= 4 ,-1 , 0
 1824.18     .15       0 3141.34     .07       0 4957.36    .032       0
 5042.64     .07       0
#XS Ineff= 2 ,-1
 3748.56 4916.19   24.66 5691.16 9266.36    26.4
Permanent Ineff=
       F       F
#Block Obstruct= 4 ,-1
 1423.65 3293.92   25.88 1844.61 4936.66   24.09 5699.94 9172.74   23.86
 7003.44 9380.02   26.27
Bank Sta=4957.36,5042.64
XS Rating Curve= 0
Exp/Cntr=.3,.1

Type RM Length L Ch R = 1 ,6054.307,1064.9,1087.82,1080.3
XS GIS Cut Line= 4
      3212694.68    13810471.112      3208825.88    13811448.288
     3208760.948     13811489.49     3204999.528     13812099.65
#Sta/Elev= 30
  970.51   21.94 1157.08   21.13  1364.4   23.68 1454.69   21.54  1511.6   23.48
 2059.81   24.69 2697.61   24.64 2784.16   22.95 2986.08   25.29 3085.67   23.54
 3748.88   24.53 3821.07   23.79 3837.33   21.24 4397.28   17.82 4836.36   17.96
 4878.99   18.73 4906.46    23.1 4961.55   22.46 4967.81    19.7 4986.56   15.88
 5015.21   16.28 5030.14   19.08 5038.45   22.65 5615.58   25.71 6465.93   24.08
 6822.61   26.24 7427.27   24.17 7550.41   25.62 8263.01   22.51  8848.3   26.79
#Mann= 4 ,-1 , 0
  970.51     .15       0  1364.4     .07       0 4967.81    .032       0
 5038.45     .07       0
#XS Ineff= 1 ,-1
 3752.86  4904.9    23.2
Permanent Ineff=
       F
#Block Obstruct= 3 ,-1
  593.79 3346.83   24.65  970.53 4911.38   23.17 5641.03  8848.3   25.67
Bank Sta=4961.55,5038.45
XS Rating Curve= 0
Exp/Cntr=.3,.1

Type RM Length L Ch R = 1 ,4966.483,747.89,783.13,820.23
XS GIS Cut Line= 4
     3212756.838     13810222.48     3208238.712    13810539.217
     3208170.516    13810574.719     3204974.664    13812000.197
#Sta/Elev= 30
  432.58   21.54   616.3   23.92  686.44   21.55  999.96   23.56 1052.99   21.77
 1294.43      25 1785.19   24.02 2030.51   26.52 2212.62   23.15 2366.65   24.99
 2407.94   23.43 2585.17    25.3 3155.61   23.28 3815.79   25.68 4536.83   23.74
 4693.13   20.98 4961.56   20.68 4982.13   15.68 5014.87   15.54 5032.59   18.67
 5038.44   21.96 5660.16   24.53 5897.46   22.88 5934.87   24.32 5974.82   22.86
  6073.7    24.3 7027.53   24.67 7425.58   22.49 7906.79   22.65 8538.03   26.96
#Mann= 4 ,-1 , 0
  432.58     .15       0  999.96     .07       0 4961.56    .032       0
 5038.44     .07       0
#XS Ineff= 2 ,-1
 4601.14 4801.92   21.46 5775.75 8187.74   24.57
Permanent Ineff=
       F       F
#Block Obstruct= 2 , 0
         4106.94   25.33 6114.73           24.34
Bank Sta=4961.56,5038.44
XS Rating Curve= 0
Exp/Cntr=.3,.1

Type RM Length L Ch R = 1 ,4183.356,40.82,40,40.11
XS GIS Cut Line= 4
     3212779.895    13810075.966     3207891.568    13809854.993
     3207825.198    13809855.373     3205039.448    13810038.625
#Sta/Elev= 30
    81.7   22.87  701.82   23.68 1041.42   24.69 1101.48   23.08 1316.67   24.36
 1400.38   23.18 1550.56   24.82 1596.98   22.57 1720.71   25.56 1845.95   23.42
 2017.41   24.86 2212.61   23.15 2407.24   25.45 2512.92      23 2741.43   25.28
 2768.18   23.97 3616.65   23.22 3901.33    24.4 4586.37   22.82 4970.71      20
 5005.53   13.21 5039.29   20.52 5118.82   22.43  5351.1    22.9 5507.79   20.76
 6648.04   25.31 7012.18   23.16 7180.69    24.2 7425.57   21.11 7833.16    21.8
#Mann= 4 ,-1 , 0
    81.7     .15       0  701.82     .07       0 4970.71    .032       0
 5039.29     .07       0
#Block Obstruct= 4 ,-1
    81.7 4313.99   23.68 5351.55 7833.12   22.37 6520.92 7730.09   24.89
 6520.92 7935.22   24.97
Bank Sta=4970.71,5039.29
XS Rating Curve= 0
Exp/Cntr=.5,.3

Type RM Length L Ch R = 1 ,4143.355,168.45,167.29,177.87
XS GIS Cut Line= 4
     3212781.701    13810036.006     3207892.357    13809814.988
     3207823.769    13809815.381     3205036.822    13809998.712
#Sta/Elev= 30
   71.13   22.21   691.6   24.15  1002.1   22.75 1328.42   24.18 1376.84   22.83
 1531.89   24.46 1588.22   22.02 1653.91   24.24 2008.65   24.68 2203.85   22.88
 2338.12   24.53 2660.39   23.47 2716.92   25.26 2788.34   23.77 3610.98   22.77
 3685.79   24.25 4266.91   24.06 4965.71      20 5000.53   13.21 5034.29   20.52
  5173.1   22.39 5342.33    22.8 5493.96   20.51 5550.14   22.01 6685.68   25.18
 6990.42   23.29 7161.26   24.72 7416.81   21.14  7560.4   22.63 7827.03    21.7
#Mann= 4 ,-1 , 0
   71.13     .15       0   691.6     .07       0 4965.71    .032       0
 5034.29     .07       0
#XS Ineff= 2 , 0
       0 4965.71    21.5 5034.29       0   20.52
Permanent Ineff=
       F       F
#Block Obstruct= 4 ,-1
   71.13 4277.59   24.01 4423.64 4560.63   22.28 5352.91  7837.5   22.33
 6488.53 7924.43   24.59
Bank Sta=4965.71,5034.29
XS Rating Curve= 0
Exp/Cntr=.5,.3

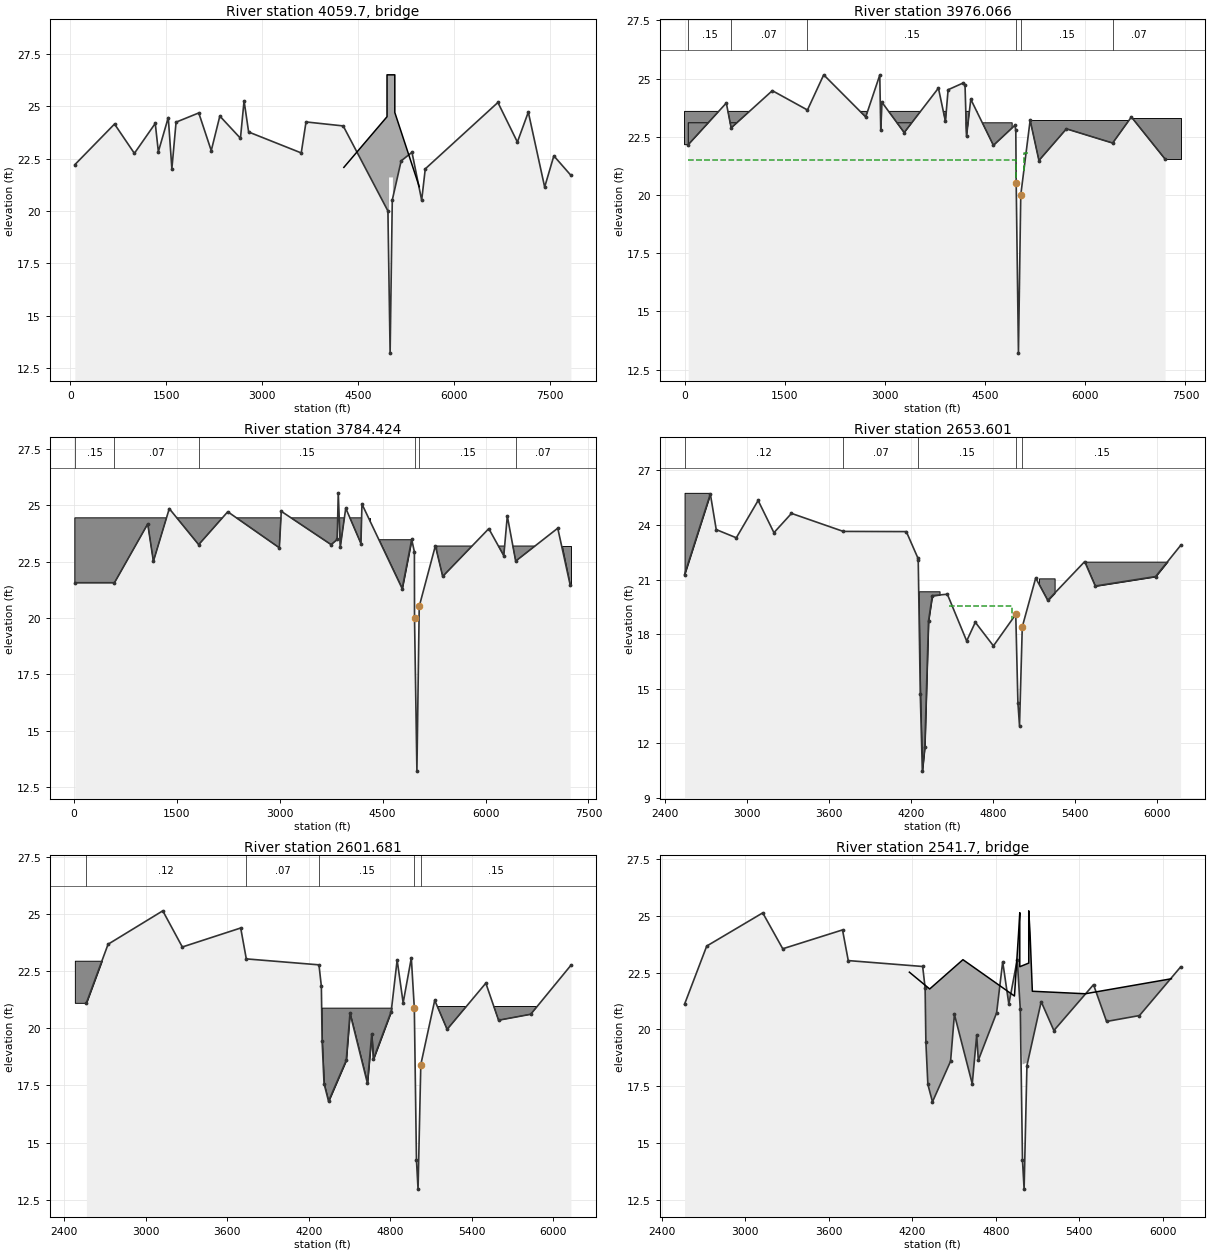
Type RM Length L Ch R = 3 ,4059.7  ,,,
Node Photo=G:\C2001-041_Harris_County_FEMA\1-Armand_Bayou\Willow Springs Bayou Trib 1.78\Survey info\Spencer - 3439\MVC-008S.JPG
BEGIN DESCRIPTION:
Spencer Highway
END DESCRIPTION:
Bridge Culvert--1,0,-1,-1, 0
Deck Dist Width WeirC Skew NumUp NumDn MinLoCord MaxHiCord MaxSubmerge Is_Ogee
51,101,2.6,0, 10, 10, , , .95, 0, 0,0,,
    4277    4952 4952.01 4983.99    4984    5044 5044.01 5073.99    5074    5456
   22.08    24.5    26.5    26.5    26.5    26.5    26.5    26.5    24.7   21.16
                       0       0    21.6    21.6       0       0
    4277    4952 4952.01 4983.99    4984    5044 5044.01 5073.99    5074    5456
   22.08    24.5    26.5    26.5    26.5    26.5    26.5    26.5    24.7   21.16
                       0       0    21.6    21.6       0       0
BR Coef=-1 , 0 , 0 ,, 0 ,,,.8,-1,,0,
WSPro=,,,, 1 ,,,, 0 ,,,, 0 ,,,,-1 ,-1 ,-1 , 0 , 0 , 0 , 0 , 0
BC Design=,, 0 ,, 0 ,,,,,,
BC HTab HWMax=25.26

Type RM Length L Ch R = 1 ,3976.066,191.48,191.64,192.04
XS GIS Cut Line= 2
      3212795.72    13809881.733      3205662.99    13809544.109
#Sta/Elev= 30
   55.06   22.16  625.26   23.95  697.72   22.88 1314.18   24.48 1840.24   23.65
 2083.55   25.16 2712.59   23.35 2923.15   25.15 2937.85   22.77  2956.1   23.98
 3289.04   22.68  3801.4   24.59  3906.3   23.16 3946.38   24.52 4172.11   24.81
 4199.57   24.73 4221.89   22.52  4285.9   24.11 4624.99   22.13 4945.87   22.99
    4960   22.78 4965.71   20.52 4999.47   13.21 5034.29      20 5174.86   23.21
 5306.35   21.48 5717.87   22.84  6410.3   22.23 6690.62   23.35 7195.78   21.54
#Mann= 6 ,-1 , 0
   55.06     .15       0  697.72     .07       0 1840.24     .15       0
 4965.71    .032       0 5034.29     .15       0  6410.3     .07       0
#XS Ineff= 2 ,-1
   55.06 4965.71    21.5 5079.52 5165.19    21.8
Permanent Ineff=
       F       F
#Block Obstruct= 4 ,-1
       0 4383.27   23.59   55.06 4905.57    23.1 5178.61 7195.78    23.2
 6693.66  7427.8   23.31
Bank Sta=4965.71,5034.29
XS Rating Curve= 0
Exp/Cntr=.5,.3

Type RM Length L Ch R = 1 ,3784.424,1391.86,1130.82,983.12
XS GIS Cut Line= 4
     3212804.185    13809721.957     3207604.392    13809446.471
     3207515.792    13809584.563     3205671.081    13809495.564
#Sta/Elev= 30
   15.96   21.57   593.4   21.57 1078.13   24.18 1160.59   22.52 1392.12   24.86
 1820.46   23.26 2244.12   24.72 2995.84   23.12 3024.07   24.74 3750.76   23.26
 3839.22   23.49 3854.36   25.56 3884.41   23.16 3963.63   24.88 4184.83   23.31
 4199.85   25.06 4785.67   21.31  4924.7   23.49    4964   22.94 4965.71      20
 5000.53   13.21 5034.29   20.52 5269.63   23.21 5376.63   21.85 6047.99   23.97
 6266.45   22.77 6317.83   24.53 6439.99   22.53 7052.83   23.99 7233.97   21.47
#Mann= 6 ,-1 , 0
   15.96     .15       0   593.4     .07       0 1820.46     .15       0
 4965.71    .032       0 5034.29     .15       0 6439.99     .07       0
#Block Obstruct= 3 ,-1
   15.96 4323.09   24.45 4359.84 4912.65    23.5 5289.18 7244.43    23.2
Bank Sta=4965.71,5034.29
XS Rating Curve= 0
Exp/Cntr=.3,.1

Type RM Length L Ch R = 1 ,2653.601,62.21,51.92,33.83
XS GIS Cut Line= 4
     3207728.419    13805954.599     3207568.808    13808361.657
     3207543.454    13808435.094     3207452.037    13809569.937
#Sta/Elev= 30
 2543.47   21.28 2732.08   25.71 2775.17   23.75 2922.06    23.3 3081.64   25.35
 3197.25   23.58 3325.69   24.64 3704.61   23.65 4165.53   23.64 4248.89   22.21
 4252.77   22.06  4267.8    14.7 4282.83   10.48 4300.87   11.82 4327.93   18.73
 4355.63   20.12  4465.7    20.2 4607.13   17.63 4670.23   18.66 4802.86   17.36
 4966.14   19.09 4981.84   14.25 4993.57   12.97 5013.86   18.41 5112.02   21.09
 5200.22   19.86 5470.15   21.99 5547.72   20.65 5988.77   21.17 6172.02   22.88
#Mann= 5 ,-1 , 0
 2543.47     .12       0 3704.61     .07       0 4248.89     .15       0
 4966.14    .032       0 5013.86     .15       0
#XS Ineff= 1 ,-1
 4479.97 4940.15   19.54
Permanent Ineff=
       F
#Block Obstruct= 5 ,-1
 2543.47 2722.98   25.77 3293.52 4173.41   23.62 4054.11 4408.74   20.36
  5136.6 5250.34   21.07 5476.11 6172.02   21.99
Bank Sta=4966.14,5013.86
XS Rating Curve= 0
Exp/Cntr=.5,.3

Type RM Length L Ch R = 1 ,2601.681,117.43,119.98,120.94
XS GIS Cut Line= 4
     3207688.534    13805951.567     3207505.557    13808357.948
      3207513.66    13808404.974     3207410.611    13809503.655
#Sta/Elev= 30
 2563.63   21.11 2722.97   23.67 3125.35   25.13 3269.25   23.55 3698.75   24.38
 3739.93   23.03 4274.61   22.77 4292.19   21.83 4297.66   19.45  4311.9   17.58
 4345.03   16.81 4475.28    18.6  4502.8   20.66 4630.98    17.6 4662.89   19.75
 4674.46   18.64 4806.03   20.73 4849.75   22.98 4893.92   21.11  4954.1   23.07
 4976.14   20.88 4991.84   14.25 5003.57   12.97 5023.86   18.41 5126.32   21.22
 5217.51   19.95 5502.29   21.97 5596.01   20.35 5832.56   20.61 6128.18   22.75
#Mann= 5 ,-1 , 0
 2563.63     .12       0 3739.93     .07       0 4274.61     .15       0
 4976.14    .032       0 5023.86     .15       0
#XS Ineff= 2 , 0
       0                 5023.86       0   18.41
Permanent Ineff=
       F       F
#Block Obstruct= 3 ,-1
 2478.41 2732.12   22.95 2563.63 4875.17    20.9 5123.21 5973.27   20.95
Bank Sta=4976.14,5023.86
XS Rating Curve= 0
Exp/Cntr=.5,.3

Type RM Length L Ch R = 3 ,2541.7  ,,,
Node Photo=G:\C2001-041_Harris_County_FEMA\1-Armand_Bayou\Willow Springs Bayou Trib 1.78\Survey info\Canada - 3487\MVC-016S.JPG
BEGIN DESCRIPTION:
Canada St.
END DESCRIPTION:
Bridge Culvert--1,0,-1,-1, 0
Deck Dist Width WeirC Skew NumUp NumDn MinLoCord MaxHiCord MaxSubmerge Is_Ogee
55,28,2.6,0, 13, 13, , , .95, 0, 0,0,,
    4179    4325    4564 4934.25 4963.42 4972.41 4972.42 5036.88 5036.89 5046.16
 5062.78    5443    6062
   22.52   21.78   23.07   21.47    24.2   25.14   22.76   22.92   25.22   24.25
   21.68   21.57   22.23
                                               0   18.41   18.57       0
                        
    4179    4325    4564 4934.25 4963.42 4972.41 4972.42 5036.88 5036.89 5046.16
 5062.78    5443    6062
   22.52   21.78   23.07   21.47    24.2   25.14   22.76   22.92   25.22   24.25
   21.68   21.57   22.23
                                               0   18.41   18.57       0
                        
BR Coef=-1 , 0 , 0 ,, 0 ,,,.8,-1,,0,
WSPro=,,,, 1 ,,,, 0 ,,,, 0 ,,,,-1 ,-1 ,-1 , 0 , 0 , 0 , 0 , 0
BC Design=,, 0 ,, 0 ,,,,,,
BC HTab HWMax=25.13