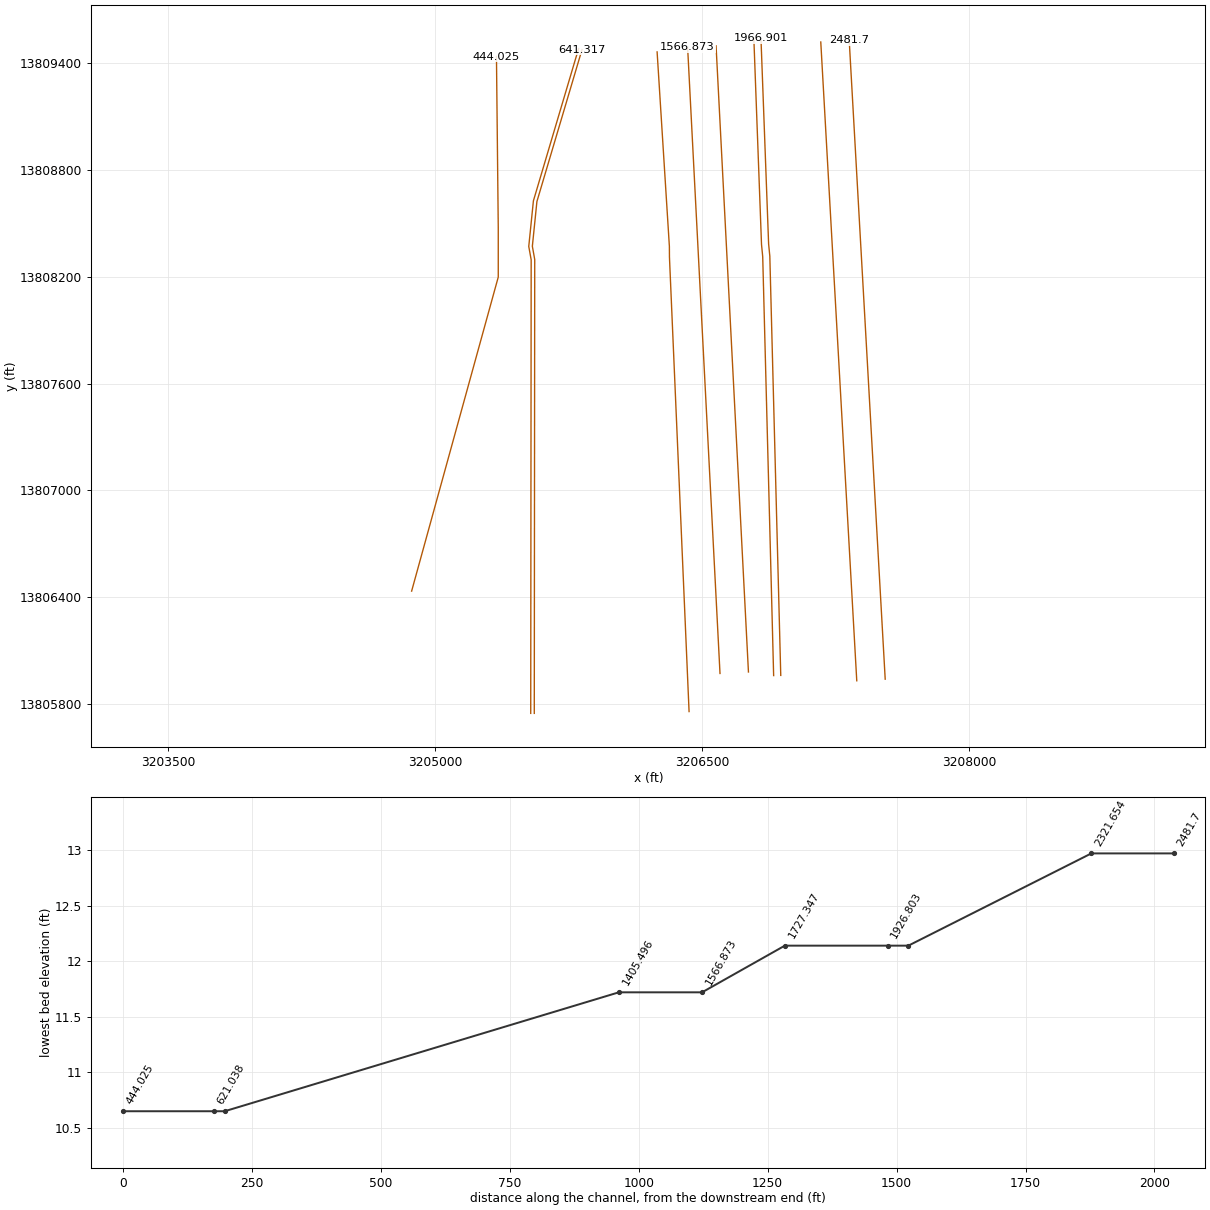
HEC-RAS study B112_02_00.prj: B112-02-00

--- B112_02_00.g02 (geometry) --- (continued)

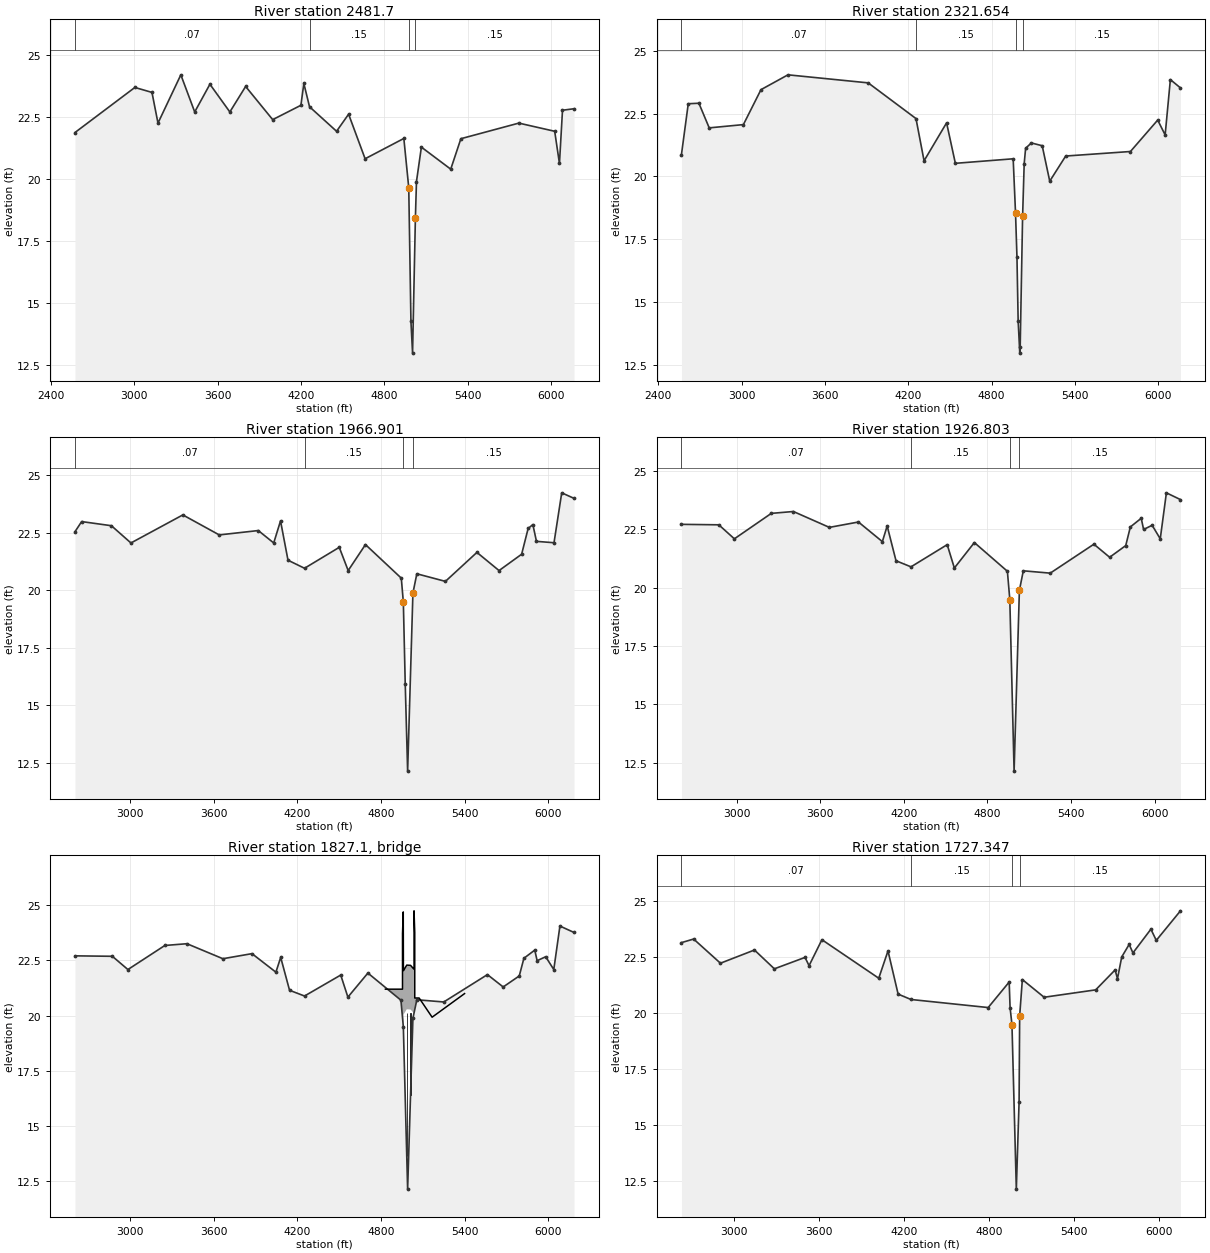
Type RM Length L Ch R = 1 ,2481.7  ,160.14,160.05,160.09
XS GIS Cut Line= 2
     3207526.785    13805939.617      3207324.63    13809527.867
#Sta/Elev= 30
 2572.29   21.88 3003.44    23.7 3126.74    23.5 3170.03   22.26 3334.59   24.21
 3434.51   22.71 3544.04   23.83 3687.62   22.71 3801.27   23.74 3996.19    22.4
 4199.39   22.98 4220.55   23.86 4261.44   22.92 4456.23   21.93  4542.9   22.62
 4661.77   20.82 4940.71   21.64 4976.14   19.65 4991.84   14.25 5003.57   12.97
 5023.86   18.41 5031.72    19.9 5067.07   21.29 5278.47    20.4 5351.52   21.63
 5768.93   22.26 6027.18   21.93 6061.47   20.63 6083.38   22.78 6166.23   22.84
#Mann= 4 ,-1 , 0
 2572.29     .07       0 4261.44     .15       0 4976.14    .032       0
 5023.86     .15       0
#XS Ineff= 2 , 0
       0                 5023.86       0   18.41
Permanent Ineff=
       F       F
#Block Obstruct= 2 , 0
                         5798.25           22.12
Bank Sta=4976.14,5023.86
XS Rating Curve= 0
Exp/Cntr=.5,.3

Type RM Length L Ch R = 1 ,2321.654,356.6,354.75,354.03
XS GIS Cut Line= 2
     3207367.038    13805930.617     3207164.883    13809518.868
#Sta/Elev= 30
  2566.9   20.87 2615.89   22.89 2692.52   22.91 2766.75   21.93 3012.93   22.06
 3139.64   23.45 3334.05   24.04 3911.81   23.72 4256.05    22.3  4314.2   20.62
 4476.41   22.13 4539.58   20.52    4956    20.7    4973   18.53 4983.26   16.79
 4991.84   14.25 5003.57   12.97 5006.43    13.2 5023.86   18.41 5035.34   20.51
 5045.72   21.12 5086.94   21.33 5165.02   21.22 5219.31   19.81  5334.3   20.81
 5800.55   20.99  5996.9   22.24 6050.51   21.65  6088.1   23.85 6160.84   23.52
#Mann= 4 ,-1 , 0
  2566.9     .07       0 4256.05     .15       0    4973    .032       0
 5023.86     .15       0
#Block Obstruct= 2 , 0
         3906.14   23.68 5089.31           21.29
Bank Sta=4973,5023.86
XS Rating Curve= 0
Exp/Cntr=.3,.1

Type RM Length L Ch R = 1 ,1966.901,40,40.1,40
XS GIS Cut Line= 4
     3206940.091    13805960.875     3206878.647    13808315.948
     3206871.887    13808384.562     3206828.892    13809539.463
#Sta/Elev= 30
 2604.64   22.55 2652.39   22.99 2865.85   22.81 3006.06   22.06 3378.51   23.28
 3639.68   22.41 3919.92    22.6 4030.57   22.06 4079.42   23.02 4133.06   21.31
 4251.68   20.96 4500.84   21.87 4564.82   20.86  4688.8   21.99    4946   20.53
 4960.64   19.49 4974.21   15.93 4991.43   12.14 5029.36   19.88 5057.46   20.72
 5262.56   20.39 5488.61   21.65 5647.34   20.86 5809.39   21.57 5856.06   22.69
 5890.03   22.86 5915.85   22.13 6041.76   22.07 6097.07   24.24 6185.16      24
#Mann= 4 ,-1 , 0
 2604.64     .07       0 4251.68     .15       0 4960.64    .032       0
 5029.36     .15       0
#Block Obstruct= 2 , 0
         3382.82   23.28 6099.54           24.24
Bank Sta=4960.64,5029.36
XS Rating Curve= 0
Exp/Cntr=.5,.3

Type RM Length L Ch R = 1 ,1926.803,198.29,199.46,199.33
XS GIS Cut Line= 4
     3206900.105    13805959.832     3206838.698    13808313.462
      3206831.96    13808381.854     3206788.919    13809537.975
#Sta/Elev= 30
 2604.93   22.71 2872.92   22.69 2984.56   22.09 3249.57   23.18 3408.06   23.26
 3666.03   22.58 3874.68   22.81 4046.33   21.97 4080.75   22.64 4144.29   21.15
 4251.76   20.89 4511.46   21.84 4562.82   20.84 4706.31   21.93 4943.34    20.7
 4960.64   19.49 4991.43   12.14 5029.36   19.88 5057.46   20.72 5250.71   20.62
 5563.89   21.86 5676.94    21.3 5792.35    21.8 5825.59    22.6 5903.52   22.97
 5920.53   22.49 5981.82   22.67 6040.02   22.09 6084.03   24.06 6185.01   23.77
#Mann= 4 ,-1 , 0
 2604.93     .07       0 4251.76     .15       0 4960.64    .032       0
 5029.36     .15       0
#XS Ineff= 2 , 0
       0 4960.64   19.49 5029.36       0   19.88
Permanent Ineff=
       F       F
#Block Obstruct= 2 , 0
         3405.57   23.23 6099.54           24.17
Bank Sta=4960.64,5029.36
XS Rating Curve= 0
Exp/Cntr=.5,.3

Type RM Length L Ch R = 3 ,1827.1  ,,,
Node Photo=G:\C2001-041_Harris_County_FEMA\1-Armand_Bayou\Willow Springs Bayou Trib 1.78\Survey info\Plantation - unknown station\MVC-007S.JPG
BEGIN DESCRIPTION:
W. Plantation
END DESCRIPTION:
Bridge Culvert--1,0,-1,-1, 0
Deck Dist Width WeirC Skew NumUp NumDn MinLoCord MaxHiCord MaxSubmerge Is_Ogee
58,52,2.6,0, 17, 17, , , .95, 0, 0,0,,
    4832    4929 4954.59  4954.6 4960.07 4961.17 4961.18 4985.06 5012.34 5036.04
 5037.45 5037.46 5042.55 5042.56    5074    5167    5400
    21.2    21.2    21.2   23.71    24.7   22.04   22.04   22.29   22.28   22.11
   22.11   24.75   23.76    20.8    20.8   19.93      21
       0       0       0       0       0       0   20.04   20.29   20.28   20.11
       0       0       0       0       0       0
    4832    4915 4940.59  4940.6 4946.07 4947.17 4947.18 4971.06 4998.34 5022.04
 5023.45 5023.46 5028.55 5028.56    5060    5167    5400
    21.2    21.2    21.2   23.71    24.7   22.04   22.04   22.29   22.28   22.11
   22.11   24.75   23.76    20.8    20.8   19.93      21
       0       0       0       0       0       0   20.04   20.29   20.28   20.11
       0       0       0       0       0       0
Pier Skew, UpSta & Num, DnSta & Num=  ,4985.06, 4 ,4974.06, 4 , 3 , 3 , 0 ,,
     1.2     1.2     2.2     2.2
      12   17.71   17.71   20.11
     1.2     1.2     2.2     2.2
      12   17.71   17.71   20.11
Pier Skew, UpSta & Num, DnSta & Num=  ,5012.34, 4 ,5001.34, 4 , 3 , 3 , 0 ,,
     1.2     1.2     2.2     2.2
      12   17.71   17.71   20.11
     1.2     1.2     2.2     2.2
      12   17.71   17.71   20.11
BR Coef=-1 , 1 , 0 ,, 0 ,,,.8,-1,1.25,0,
WSPro=,,,, 1 ,,,, 0 ,,,, 0 ,,,,-1 ,-1 ,-1 , 0 , 0 , 0 , 0 , 0
BC Design=,, 0 ,, 0 ,,,,,,
BC HTab HWMax=24.16

Type RM Length L Ch R = 1 ,1727.347,160.11,160.47,160.06
XS GIS Cut Line= 2
     3206758.596    13805980.048     3206576.657    13809497.544
#Sta/Elev= 30
  2627.8   23.15 2713.82   23.31 2903.03   22.23 3143.07   22.82 3283.55   21.98
 3500.05   22.49 3528.47   22.12 3619.23   23.28  4020.4   21.56 4085.64   22.78
 4157.08   20.85 4248.01   20.61 4792.81   20.25 4940.99   21.39  4947.3   20.25
 4960.64   19.49 4991.43   12.14 5010.95   16.05    5015   19.88    5034    21.5
 5187.54   20.71 5551.65   21.04 5688.59   21.93 5705.47   21.54  5735.4   22.51
 5787.92   23.07 5814.55   22.69 5941.27   23.75 5979.29   23.25    6150   24.57
#Mann= 4 ,-1 , 0
  2627.8     .07       0 4248.01     .15       0 4960.64    .032       0
    5015     .15       0
#XS Ineff= 2 , 0
       0 4960.64   19.49    5015       0   19.88
Permanent Ineff=
       F       F
#Block Obstruct= 2 , 0
         4083.62   24.37    5781           25.03
Bank Sta=4960.64,5015
XS Rating Curve= 0
Exp/Cntr=.5,.3

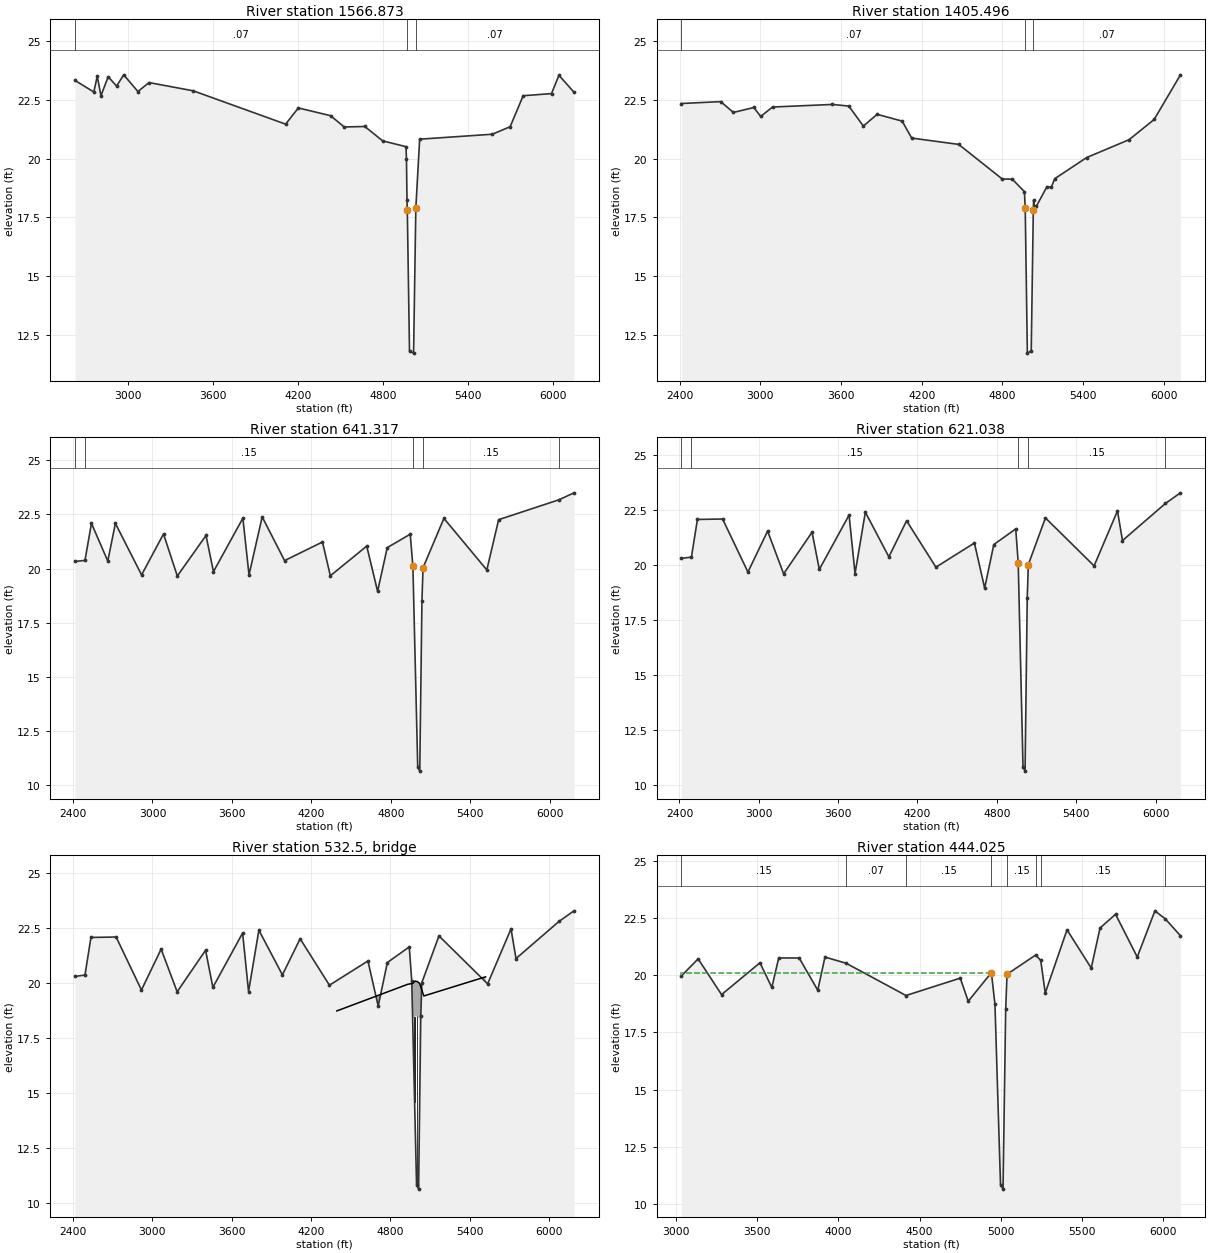
Type RM Length L Ch R = 1 ,1566.873,163.71,161.38,161.64
XS GIS Cut Line= 2
      3206598.81    13805971.783      3206416.87    13809489.279
#Sta/Elev= 30
 2624.28   23.33  2757.2   22.84 2781.35   23.51 2807.53   22.68 2858.69   23.49
 2918.04   23.09 2968.22   23.57 3068.42   22.86 3147.04   23.24 3458.54   22.89
 4111.02   21.47 4200.96   22.16 4428.36   21.83 4524.33   21.35 4669.92   21.37
 4795.55   20.76 4960.77   20.51 4963.98   19.97 4967.67   18.23 4969.93   17.82
  4985.4   11.81 5014.19   11.72 5030.07    17.9  5057.1   20.83 5569.27   21.04
 5695.75   21.36 5787.62   22.68 5987.72   22.77 6040.13   23.55 6146.48   22.83
#Mann= 3 ,-1 , 0
 2624.28     .07       0 4969.93    .015       0 5030.07     .07       0
#Block Obstruct= 2 , 0
         2977.82   23.85 6035.84           23.75
Bank Sta=4969.93,5030.07
XS Rating Curve= 0
Exp/Cntr=.3,.1

Type RM Length L Ch R = 1 ,1405.496,761.16,764.18,750.04
XS GIS Cut Line= 4
      3206425.04    13805757.677     3206314.867    13808310.235
     3206314.448    13808370.381      3206245.53    13809463.201
#Sta/Elev= 30
 2414.08   22.34 2705.32   22.42 2800.68   21.96 2952.41   22.17 3003.05   21.79
 3091.32   22.19 3536.58    22.3 3658.45   22.23 3766.49   21.38 3869.07   21.88
 4055.04   21.59 4125.66   20.87 4475.14    20.6 4798.77   19.13 4873.97   19.12
 4963.93   18.59 4969.93    17.9 4985.81   11.72  5014.6   11.81 5030.07   17.82
 5032.33   18.23 5038.95   17.93 5052.91   17.97 5131.29    18.8    5164   18.78
 5189.25   19.14 5426.43   20.04 5741.99    20.8 5928.38   21.66 6124.15   23.56
#Mann= 3 ,-1 , 0
 2414.08     .07       0 4969.93    .015       0 5030.07     .07       0
Bank Sta=4969.93,5030.07
XS Rating Curve= 0
Exp/Cntr=.3,.1

Type RM Length L Ch R = 1 ,641.317 ,20,20.28,20.16
XS GIS Cut Line= 5
     3205555.559     13805747.55     3205558.072    13808297.054
     3205544.728    13808371.359      3205570.32    13808622.742
     3205823.623    13809476.102
#Sta/Elev= 30
 2415.26   20.33 2490.62   20.38 2539.59   22.09 2662.86   20.35 2720.26   22.09
 2917.86   19.71 3083.68    21.6 3187.86   19.66 3404.56   21.53 3460.78   19.86
 3682.86   22.33 3729.29   19.71 3828.77   22.39 3997.86   20.37  4283.9   21.23
 4343.35   19.67 4618.13   21.04  4700.2   18.95 4773.03   20.97 4946.51   21.59
 4966.74   20.11 5003.08   10.85 5018.47   10.65 5034.92   18.51 5043.26   20.04
 5200.93   22.32 5524.85   19.94 5614.08   22.26 6070.07   23.18  6183.1    23.5
#Mann= 5 ,-1 , 0
 2415.26     .07       0 2490.62     .15       0 4966.74    .015       0
 5043.26     .15       0 6070.07     .07       0
#Block Obstruct= 2 , 0
         4445.96   23.19  5202.5           23.19
Bank Sta=4966.74,5043.26
XS Rating Curve= 0
Exp/Cntr=.5,.3

Type RM Length L Ch R = 1 ,621.038 ,184.81,177.01,183.03
XS GIS Cut Line= 5
     3205535.559    13805747.569      3205538.07    13808295.282
     3205524.547     13808370.59     3205550.613    13808626.635
      3205804.45    13809481.793
#Sta/Elev= 30
 2415.07   20.32 2490.54   20.38 2535.75   22.09  2726.2   22.11 2917.65    19.7
 3066.54   21.56 3187.65   19.62 3402.68   21.51 3457.71   19.82 3682.65   22.29
 3727.65   19.63 3805.68   22.42  3983.6   20.39 4117.65   22.03 4339.23   19.92
 4630.41   21.02 4707.99   18.97 4777.27   20.95 4942.97   21.66 4961.74   20.11
 4998.08   10.85 5013.47   10.65 5029.92   18.51 5038.26   20.04 5167.58   22.16
 5535.59   19.98 5712.37   22.48 5750.12   21.13 6075.49   22.82  6188.7    23.3
#Mann= 5 ,-1 , 0
 2415.07     .07       0 2490.54     .15       0 4961.74    .015       0
 5038.26     .15       0 6075.49     .07       0
#XS Ineff= 2 , 0
       0 4961.74   20.11 5038.26       0   20.04
Permanent Ineff=
       F       F
#Block Obstruct= 2 , 0
         4127.42   23.59    5157           23.57
Bank Sta=4961.74,5038.26
XS Rating Curve= 0
Exp/Cntr=.5,.3

Type RM Length L Ch R = 3 ,532.5   ,,,
Node Photo=G:\C2001-041_Harris_County_FEMA\1-Armand_Bayou\Willow Springs Bayou Trib 1.78\Survey info\Somerton - 3455\MVC-024S.JPG
BEGIN DESCRIPTION:
Somerton
END DESCRIPTION:
Bridge Culvert--1,0,-1,-1, 0
Deck Dist Width WeirC Skew NumUp NumDn MinLoCord MaxHiCord MaxSubmerge Is_Ogee
77,45,2.6,0, 10, 10, , , .95, 0, 0,0,,
    4395    4931 4968.68 4968.69  4987.2 5004.89 5021.61 5021.62    5053    5520
   18.75   19.96      20      20   20.11   20.08      20      20   19.43    20.3
       0       0       0    18.4    18.5    18.5    18.4       0       0       0
    4395    4931 4968.68 4968.69  4987.2 5004.89 5021.61 5021.62    5053    5520
   18.75   19.96      20      20   20.11   20.08      20      20   19.43    20.3
       0       0       0    18.4    18.5    18.5    18.4       0       0       0
Pier Skew, UpSta & Num, DnSta & Num=  ,4983.4, 4 ,4983.4, 4 , 3 , 3 , 0 ,,
     1.2     1.2     1.9     1.9
      10   17.51   17.51   18.51
     1.2     1.2     1.9     1.9
      10   17.51   17.51   18.51
Pier Skew, UpSta & Num, DnSta & Num=  ,5004, 4 ,5004, 4 , 3 , 3 , 0 ,,
     1.2     1.2     1.9     1.9
      10   17.51   17.51   18.51
     1.2     1.2     1.9     1.9
      10   17.51   17.51   18.51
BR Coef=-1 , 1 , 0 ,, 0 ,,,.8,-1,2,0,
WSPro=,,,, 1 ,,,, 0 ,,,, 0 ,,,,-1 ,-1 ,-1 , 0 , 0 , 0 , 0 , 0
BC Design=,, 0 ,, 0 ,,,,,,
BC HTab HWMax=23.3

Type RM Length L Ch R = 1 ,444.025 ,83.22,80,80.01
XS GIS Cut Line= 4
     3204866.576    13806434.367     3205353.188    13808198.336
     3205353.188    13808476.872     3205343.078    13809437.319
#Sta/Elev= 30
 3035.91   19.97 3138.46   20.71 3282.57   19.15 3518.68   20.54 3591.71   19.46
 3633.95   20.75 3759.83   20.75 3874.21   19.34 3918.47   20.79 4048.64   20.52
 4416.91   19.11 4750.38   19.87 4799.58   18.86    4942   20.11    4964   18.72
 4998.08   10.85 5013.47   10.65 5029.92   18.51 5038.26   20.04 5214.82   20.88
 5245.51   20.64 5273.21   19.22 5407.08   21.98 5556.01   20.31 5610.23   22.06
 5705.57   22.66 5839.15   20.79 5947.63   22.81 6012.74   22.45  6104.8   21.72
#Mann= 8 ,-1 , 0
 3035.91     .15       0 4048.64     .07       0 4416.91     .15       0
    4942    .015       0 5038.26     .15       0 5214.82     .07       0
 5245.51     .15       0 6012.74     .07       0
#XS Ineff= 2 , 0
       0    4942   20.11 5038.26       0   20.04
Permanent Ineff=
       F       F
#Block Obstruct= 2 , 0
         4094.99   22.47  5166.1           22.57
Bank Sta=4942,5038.26
XS Rating Curve= 0
Exp/Cntr=.5,.3