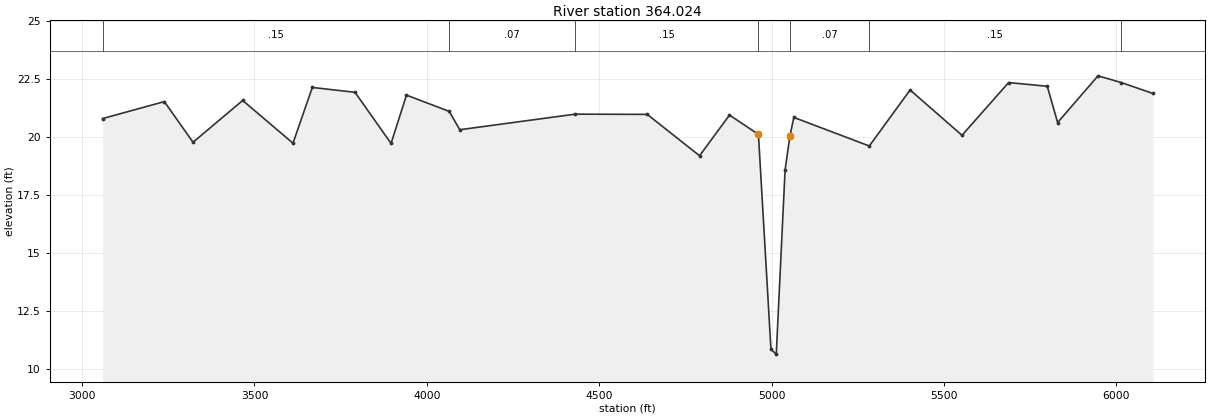
HEC-RAS study B112_02_00.prj: B112-02-00

--- B112_02_00.g02 (geometry) --- (continued)

Type RM Length L Ch R = 1 ,364.024 ,405.79,364.02,387.2
XS GIS Cut Line= 4
     3204789.456    13806455.641     3205273.188    13808209.168
     3205273.188    13808476.451     3205263.083    13809436.477
#Sta/Elev= 30
 3059.45   20.79 3238.64   21.52 3321.87   19.77  3465.8   21.57 3611.75   19.73
 3667.85   22.13 3791.72   21.92 3896.18   19.72 3940.97    21.8 4064.76    21.1
 4095.48   20.31 4430.32   20.98 4639.26   20.97 4790.95   19.19 4877.79   20.94
 4961.74   20.11 4998.08   10.85 5013.47   10.65    5039   18.57    5053   20.04
 5064.46   20.84 5283.31   19.61 5401.69   22.02 5552.18   20.07 5687.39   22.34
  5799.5   22.18  5829.5   20.62 5946.65   22.63 6014.45   22.34 6105.84   21.87
#Mann= 7 ,-1 , 0
 3059.45     .15       0 4064.76     .07       0 4430.32     .15       0
 4961.74    .015       0    5053     .07       0 5283.31     .15       0
 6014.45     .07       0
#Block Obstruct= 2 , 0
         4298.07    22.8 5397.04           22.91
Bank Sta=4961.74,5053
XS Rating Curve= 0
Exp/Cntr=.3,.1

Chan Stop Cuts=-1

--- B112_02_00.g03 (geometry) ---

Geom Title=B112-02-00 June 2007 (Floodway)
Version=Version 3.0.1  Mar 2001

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
River Reach=B112-02-00      ,B112-02-00_0004